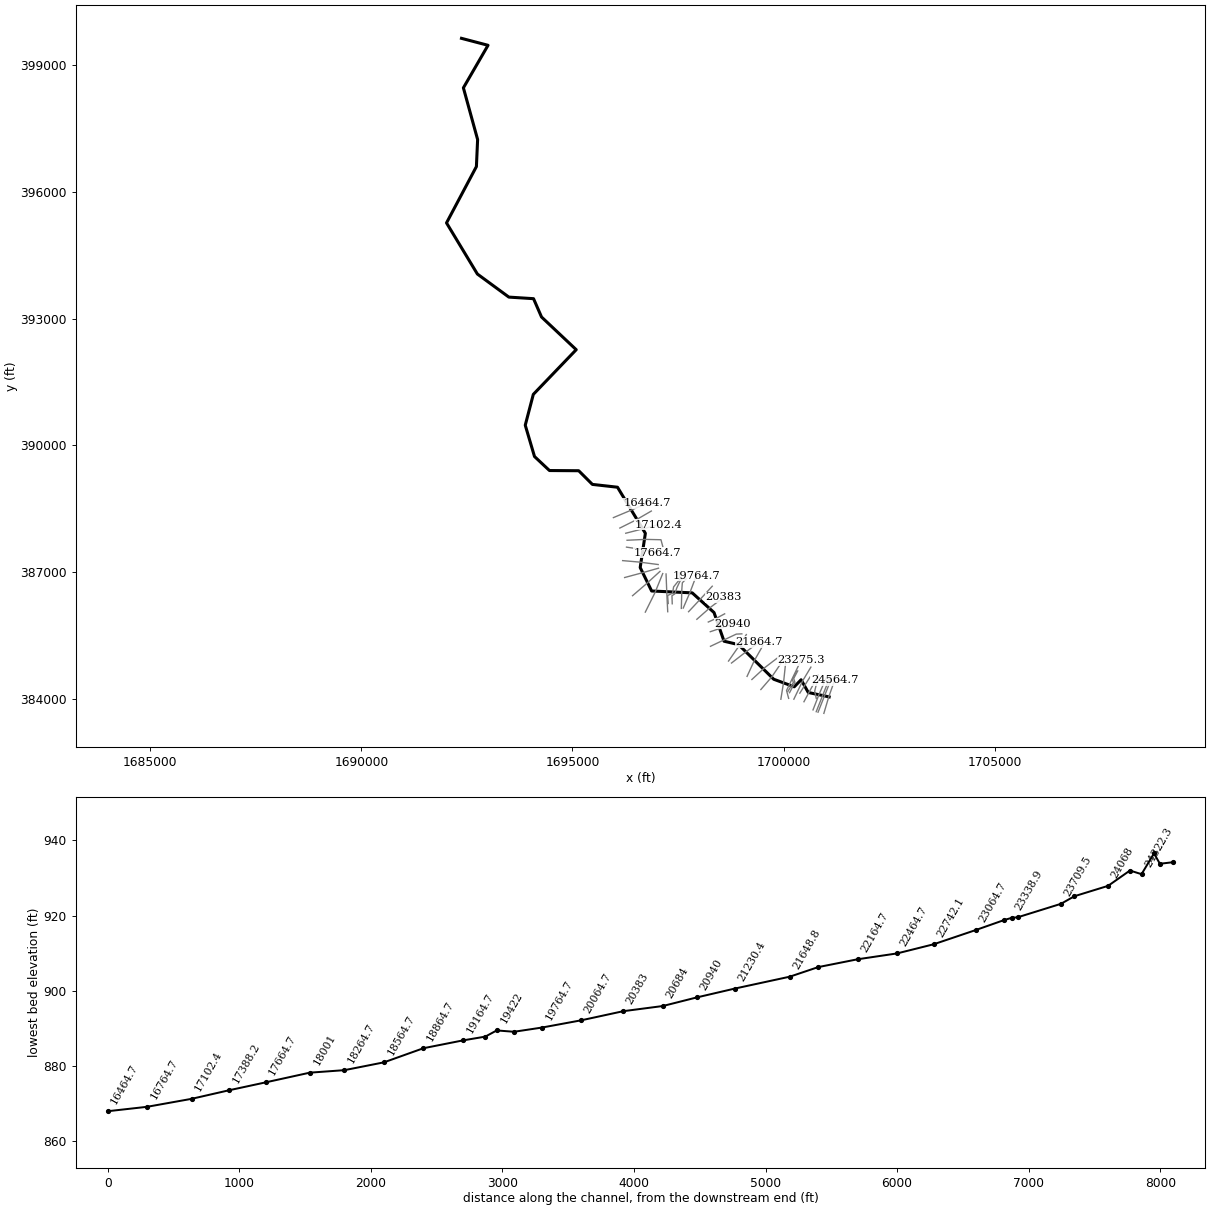
--- MUDRV.prj (project) ---

Proj Title=MUDRV
Current Plan=p01
Default Exp/Contr=0,0
English Units
Geom File=g01
Flow File=f01
Plan File=p01
BEGIN DESCRIPTION:
END DESCRIPTION:
DSS Export Rating Curves= 0
DSS Export Rating Curve Sorted= 0
DSS Export Volume Flow Curves= 0
DXF OffsetX= 0
DXF OffsetY= 0
DXF ScaleX= 0
DXF ScaleY= 0

--- MUDRV.p01 (plan) ---

Plan Title=Floodplain
Program Version=4.00
Geom File=g01
Flow File=f01
K Sum by GR=0
Std Step Tol=0.01
Critical Tol=0.01
Num of Std Step Trials=20
Max Error Tol=0.3
Flow Tol Ratio=0.001
Split Flow NTrial=30
Split Flow Tol=0.02
Split Flow Ratio=0.02
Log Output Level=0
Friction Slope Method=1
Unsteady Friction Slope Method=2
Unsteady Bridges Friction Slope Method=1
Global Log Level=0
CheckData=False
Run HTab=0
Run UNet=0
Run PostProcess=0
UNET Theta=0
UNET Theta Warmup=0
UNET ZTol=0
UNET ZSATol=0
UNET MxIter=0
UNET MaxInSteps=0
UNET DtIC=0
UNET DtMin=0
UNET MaxCRTS=0
UNET WFStab=0
UNET SFStab=0
UNET WFX=0
UNET SFX=0
UNET DSS MLevel=0
UNET DZMax Abort=0
UNET Convert EG Bridges=0
UNET Use Existing IB Tables=0
UNET Froude Limit=0
UNET Froude Power=0
Write IC File=0
Echo Input=False
Echo Output=False
Write Detailed=0

--- MUDRV.f01 (steady flow) ---

Flow Title=NFF Regression Equation
Program Version=4.10
Number of Profiles= 1
Profile Names=P100yr
River Rch & RM=MUDRV,Main            ,24564.7
920.4626
River Rch & RM=MUDRV,Main            ,22464.7
1149.504
River Rch & RM=MUDRV,Main            ,20940
1229.281
River Rch & RM=MUDRV,Main            ,18564.7
1341.705
River Rch & RM=MUDRV,Main            ,14064.7
 1432.14
River Rch & RM=MUDRV,Main            ,13464.7
1885.882
River Rch & RM=MUDRV,Main            ,10802.8
2011.541
River Rch & RM=MUDRV,Main            ,9864.7
 2481.18
River Rch & RM=MUDRV,Main            ,3864.7
2630.764
River Rch & RM=MUDRV,Main            ,3264.7
2927.495
Boundary for River Rch & Prof#=MUDRV,Main            , 1
Up Type= 0
Dn Type= 3
Dn Slope=0.00286
DSS Import GetInterval= 0
DSS Import GetPeak= 0
DSS Import FillOption= 0

--- MUDRV.g01 (geometry) ---

Geom Title=USGS 10m DEM
Program Version=4.10

River Reach=MUDRV           ,Main
Reach XY= 30
     1701081.791      384042.676     1700586.775      384147.602
     1700416.983      384448.816     1700254.657       384282.15
     1699768.546      384460.969     1698935.212      385281.282
     1698591.463      385362.011     1698354.483      386041.004
      1697837.99       386507.15     1696876.532      386551.421
     1696605.699       387107.15     1696728.094      387917.914
     1696068.025       389009.32     1695473.407       389076.16
     1695149.101      389399.945      1694456.74      389404.285
     1694102.293      389736.422      1693883.11      390478.523
     1694074.081      391208.384     1695090.314      392266.891
     1694268.613       393041.11     1694079.377      393475.137
     1693494.915       393512.29     1692749.168      394059.079
     1692018.179      395269.842     1692726.165      396604.044
     1692754.811      397244.582     1692418.005      398468.974
     1693001.252      399476.613      1692372.78      399641.544

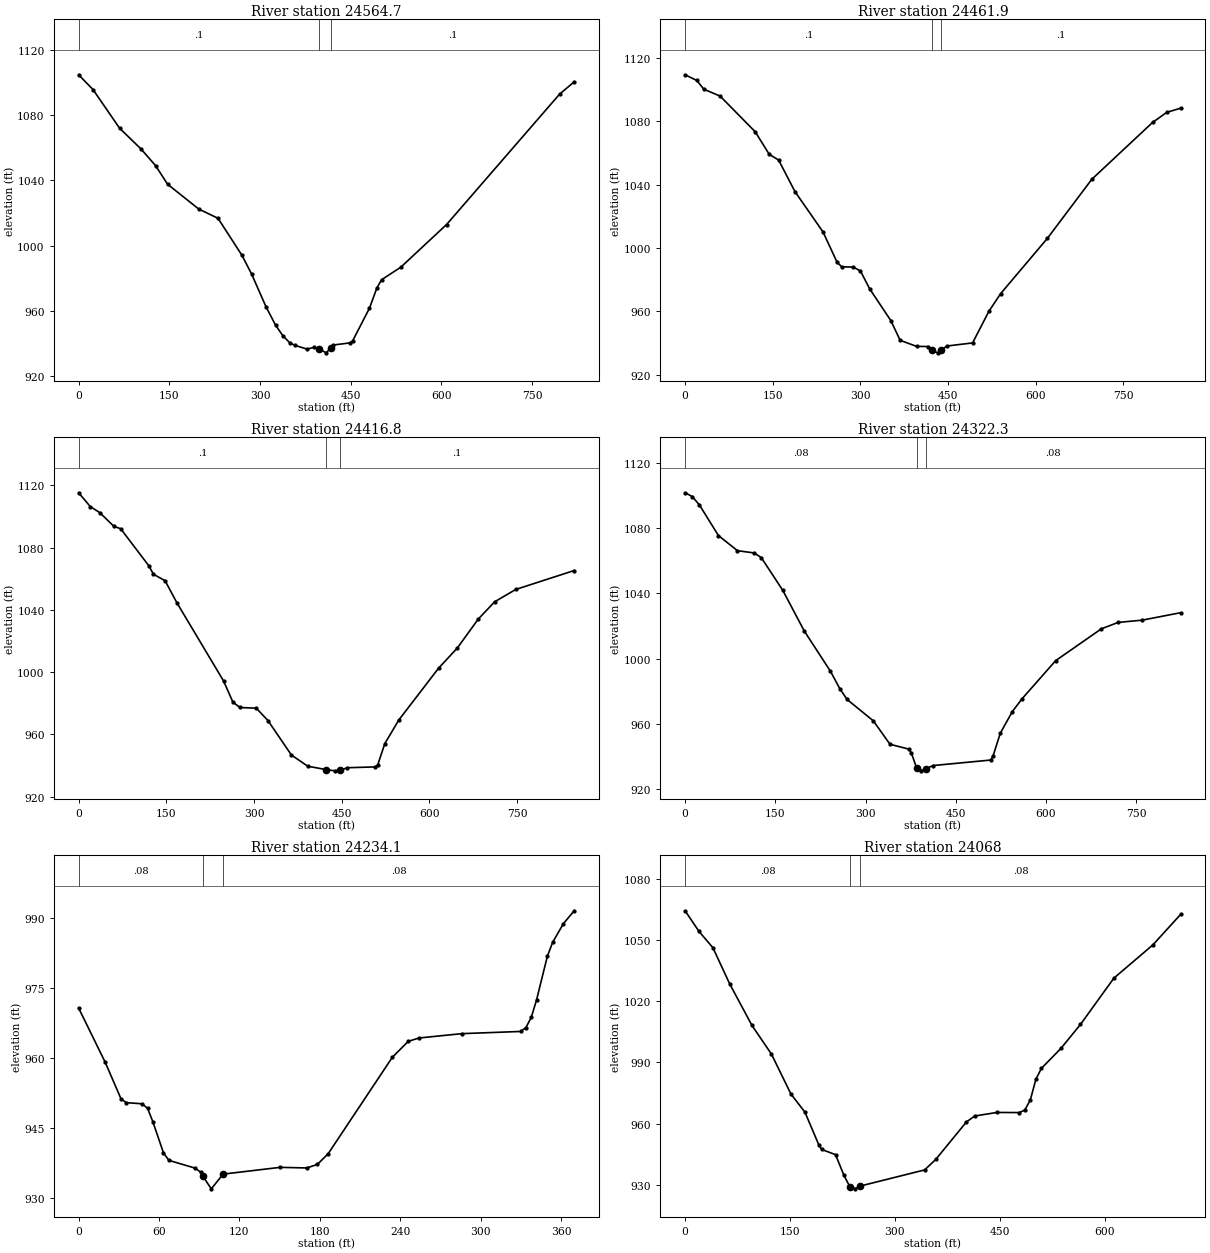
Type RM Length L Ch R = 1 ,24564.7 ,106.1,102.9,101.5
XS GIS Cut Line= 3
     1700956.015      383652.644     1701072.176      384045.163
     1701209.526      384431.667
#Sta/Elev= 30
       0 1104.74    23.8 1095.66    67.6 1072.04   103.3 1059.19   127.2 1049.06
     147 1037.66   198.7 1022.39   230.5 1016.75   270.2  993.96   286.1   982.5
     310  962.38   325.9  951.06   337.8  944.67   349.7  940.23   357.7  938.81
   377.6  936.55   389.5  937.58   397.4  936.66   409.4  934.23   416.8  937.22
   421.3  939.03   449.2  940.35   453.2  941.62     481  961.63     493   973.8
   500.9  979.04   532.8  986.74   608.5 1012.92   795.6 1092.96   819.5 1100.39
#Mann= 3 , 0 , 0
       0      .1       0   397.4    .045       0   416.8      .1       0
Bank Sta=397.4,416.8
XS Rating Curve= 0 ,0
Exp/Cntr=0.3,0.1

Type RM Length L Ch R = 1 ,24461.9 ,45.1,45,45.1
XS GIS Cut Line= 2
     1700818.171      383680.264     1701130.671      384468.458
#Sta/Elev= 30
       0 1109.52      20 1105.94      32 1100.43      60 1096.02     120 1073.49
     144 1059.24     160 1055.65     188 1035.69     236 1010.19     260  991.08
     268  988.18     288  987.98     300  985.54     316  974.13     352  954.19
     368   941.7     396   937.9   415.9  937.78   423.1  935.36   431.9   933.8
   438.1  935.42   447.9   938.1   491.9  940.07   519.9   960.1   539.9   971.2
   619.9 1006.15   695.9 1043.48   799.9 1079.41   823.9 1085.72   847.9 1088.41
#Mann= 3 , 0 , 0
       0      .1       0   423.1    .045       0   438.1      .1       0
Bank Sta=423.1,438.1
XS Rating Curve= 0 ,0
Exp/Cntr=0.3,0.1

Type RM Length L Ch R = 1 ,24416.8 ,94,94.6,92.9
XS GIS Cut Line= 2
     1700774.768      383692.417     1701087.268      384480.611
#Sta/Elev= 30
       0  1115.3      20 1106.41      36  1102.6      60 1093.84      72 1092.15
     120 1068.43     128 1062.94     148 1058.75     168 1044.67     248  994.32
     264  980.71     276  977.28     304  976.83     324  968.86     364  946.76
     392  939.53   423.5  937.36   438.5  936.56   447.9     937   459.9  938.56
   507.9  939.09   511.9   940.5   523.9  954.08   547.9  969.27   615.9 1002.55
   647.9  1015.5   683.9 1034.17   711.9 1045.24   747.9 1053.15   847.9 1065.32
#Mann= 3 , 0 , 0
       0      .1       0   423.5    .045       0   447.9      .1       0
Bank Sta=423.5,447.9
XS Rating Curve= 0 ,0
Exp/Cntr=0.3,0.1

Type RM Length L Ch R = 1 ,24322.3 ,65.6,88.2,112.2
XS GIS Cut Line= 3
     1700699.067      383735.367       1700841.1      384100.797
     1701013.164      384496.651
#Sta/Elev= 30
       0 1101.78    11.9 1099.48    23.8 1094.31    55.4 1075.52    87.1 1066.21
   114.8 1064.84   126.7 1061.95   162.4 1041.85     198 1016.96   241.6  992.18
   257.4  981.34   269.3  974.85   312.9  961.72   340.6  947.34   372.3  944.33
   376.2  941.91   384.8  932.79   392.1  931.03   399.8  932.27     412  934.27
     508  937.66     512  940.32     524   954.2   543.9  967.39   559.9  975.21
   615.9  998.68   691.8 1018.21   719.8 1022.17   759.8 1023.56   823.7 1028.15
#Mann= 3 , 0 , 0
       0     .08       0   384.8    .045       0   399.8     .08       0
Bank Sta=384.8,399.8
XS Rating Curve= 0 ,0
Exp/Cntr=0.3,0.1

Type RM Length L Ch R = 1 ,24234.1 ,192.5,166,138.8
XS GIS Cut Line= 3
     1700776.241      384008.407     1700738.914      384178.546
     1700784.921       384368.65
#Sta/Elev= 30
       0   970.7    19.8  959.11    31.7  951.22    35.6  950.45    47.5   950.2
    51.5   949.2    55.4  946.36    63.3  939.72    67.3   938.1    87.1  936.42
      91  935.56    92.8  934.66      99     932   107.8  935.15   150.4   936.6
   170.2  936.47   178.2  937.23   186.2  939.51   234.1  960.16     246  963.57
     254  964.29     286  965.22   329.9  965.69   333.8  966.53   337.8   968.7
   341.8  972.52   349.8   981.8   353.8   984.8   361.8  988.78   369.8  991.52
#Mann= 3 , 0 , 0
       0     .08       0    92.8    .045       0   107.8     .08       0
Bank Sta=92.8,107.8
XS Rating Curve= 0 ,0
Exp/Cntr=0.3,0.1

Type RM Length L Ch R = 1 ,24068   ,257.1,255.8,252.1
XS GIS Cut Line= 3
     1700484.223      383928.076     1700598.927      384142.393
     1700822.765      384550.905
#Sta/Elev= 30
       0 1064.54    19.9 1054.39    39.8 1046.38    63.8 1028.62    95.6 1008.23
   123.5  994.14   151.4   974.5   171.4  965.62   191.3  949.53   195.3  947.29
   215.2  944.71   227.1  934.66   235.6  928.99   243.1  927.92   250.6   929.3
   342.6  937.21   358.5  942.34   402.3  960.72   414.3  963.71   446.1  965.45
     478  965.39   485.9  966.59   493.9  971.62   501.9  981.84   509.8  987.14
   537.7  996.95   565.6 1008.69   613.4 1031.45   669.1 1047.75   708.9 1062.76
#Mann= 3 , 0 , 0
       0     .08       0   235.6    .045       0   250.6     .08       0
Bank Sta=235.6,250.6
XS Rating Curve= 0 ,0
Exp/Cntr=0.3,0.1

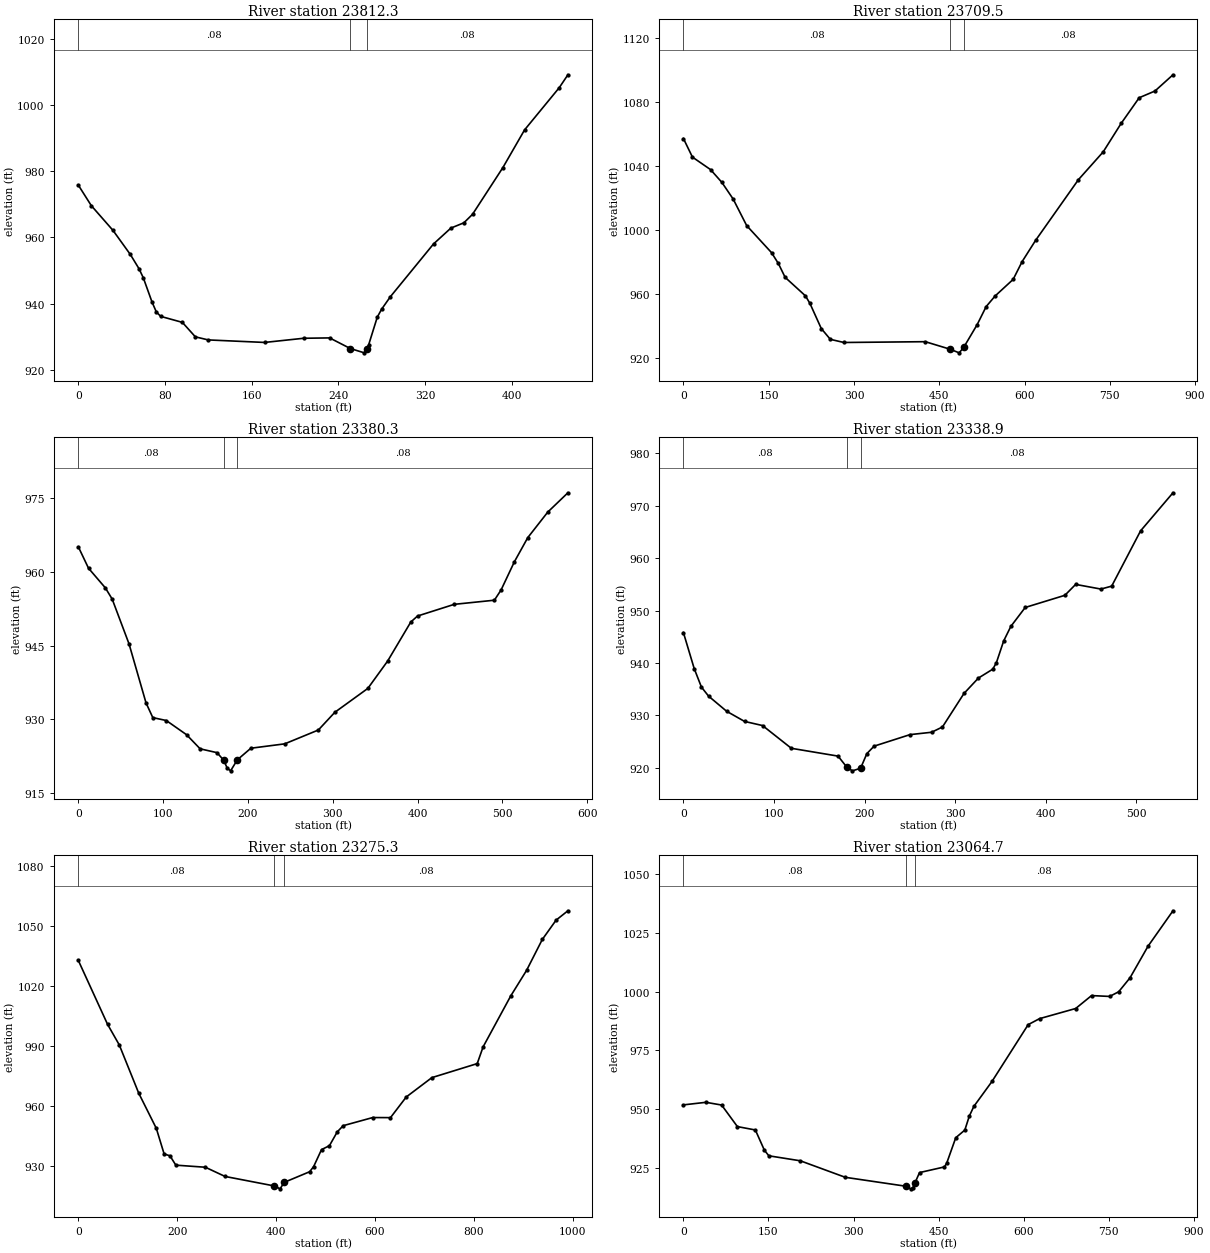
Type RM Length L Ch R = 1 ,23812.3 ,98.2,102.8,103.3
XS GIS Cut Line= 2
     1700386.484      384131.671     1700627.803      384513.615
#Sta/Elev= 30
       0   975.8      12   969.6      32  962.13      48  954.86      56  950.56
      60  947.79      68   940.5      72   937.5      76  936.17      96  934.36
     108  929.99   119.9  929.06   171.9   928.3   207.9  929.56   231.9  929.67
     251  926.46   263.9  925.16     266  926.42   267.9  927.56   275.9  935.96
   279.9  938.34   287.9  942.08   327.8  958.05   343.8  962.83   355.8  964.43
   363.8     967   391.8  981.11   411.8  992.48   443.8 1005.23   451.8 1009.13
#Mann= 3 , 0 , 0
       0     .08       0     251    .045       0     266     .08       0
Bank Sta=251,266
XS Rating Curve= 0 ,0
Exp/Cntr=0.3,0.1

Type RM Length L Ch R = 1 ,23709.5 ,331.9,329.1,313.9
XS GIS Cut Line= 3
     1700245.508       383988.84     1700453.094      384422.775
     1700649.154      384748.388
#Sta/Elev= 30
       0  1057.1    15.9 1045.46    47.7 1037.67    67.6 1029.69    87.5 1019.26
   111.3 1002.65     155  985.75     167  978.98   178.9  970.33   214.7  958.73
   222.6  953.97   242.5  938.31   258.4  931.57   282.3   929.6   425.4   930.1
   469.1  925.39     485  923.13   492.9  926.48   516.7  940.77   532.5  952.04
   548.3  958.68     580  969.05   595.8  980.18   619.6  993.51   694.8 1031.38
   738.4 1048.76     770 1066.58   801.7 1082.59   829.4 1086.78   861.1 1096.93
#Mann= 3 , 0 , 0
       0     .08       0   469.1    .045       0   492.9     .08       0
Bank Sta=469.1,492.9
XS Rating Curve= 0 ,0
Exp/Cntr=0.3,0.1

Type RM Length L Ch R = 1 ,23380.3 ,42.8,41.4,39.4
XS GIS Cut Line= 4
     1700142.535      384142.142     1700271.658      384385.197
     1700241.276      384477.428     1700336.762      384658.635
#Sta/Elev= 30
       0  965.12      12  960.77    31.9  956.76    39.9  954.49    59.8  945.36
    79.8  933.37    87.8  930.37   103.7  929.78   127.6  926.89   143.6  924.02
   163.5  923.24   171.5  921.68   175.5  920.09   179.5  919.54   187.5  921.79
   203.4  924.14   243.3  925.03     283  927.85   302.4  931.45   341.3  936.31
   364.6  941.86     392  949.83   399.9  951.04   443.2  953.42   490.5  954.26
   498.4  956.34   514.1  962.08   529.9     967   553.5   972.2   577.2  976.12
#Mann= 3 , 0 , 0
       0     .08       0   171.5    .045       0   187.5     .08       0
Bank Sta=171.5,187.5
XS Rating Curve= 0 ,0
Exp/Cntr=0.3,0.1

Type RM Length L Ch R = 1 ,23338.9 ,59.9,63.6,67.6
XS GIS Cut Line= 4
     1700104.557      384173.609     1700234.766      384387.367
     1700207.639      384453.557      1700306.38      384648.869
#Sta/Elev= 30
       0  945.82    11.9  938.96    19.9  935.42    27.8  933.69    47.7  930.81
    67.5  928.87    87.4  928.08   119.2  923.74   170.8  922.25   180.7  920.09
   186.7  919.44   195.7  919.94   202.6  922.72   210.6  924.15   250.3  926.35
   274.1   926.8   286.1  927.81   309.9  934.21   325.8  937.14   341.7  938.84
   345.7  940.09   353.7  944.22   361.6  946.99   377.5  950.61   421.3  952.93
   433.2  955.01   461.1  954.12     473  954.68   504.9  965.22   540.7  972.49
#Mann= 3 , 0 , 0
       0     .08       0   180.7    .045       0   195.7     .08       0
Bank Sta=180.7,195.7
XS Rating Curve= 0 ,0
Exp/Cntr=0.3,0.1

Type RM Length L Ch R = 1 ,23275.3 ,190.7,210.6,223.6
XS GIS Cut Line= 4
      1700121.81      384008.371     1700071.897      384195.003
     1700163.799      384384.856     1700416.949      384913.319
#Sta/Elev= 30
       0 1032.66    59.1 1000.82    82.8  990.55   122.2  966.45   157.7  948.94
   173.5  936.18   185.3  935.25   197.2  930.59   256.9  929.55   296.7  924.96
   396.6  920.21   408.1  918.78   416.1  921.98   467.9  927.32   475.9  929.88
   491.8  938.34   507.8  940.29   523.7  947.21   535.7  950.28   595.4  954.33
   631.3  954.29   663.2  964.59     715  974.24   806.7  981.23   818.7  989.62
   874.5 1014.98   906.4 1027.67   938.3 1043.13   966.2 1052.77   990.1 1057.44
#Mann= 3 , 0 , 0
       0     .08       0   396.6    .045       0   416.1     .08       0
Bank Sta=396.6,416.1
XS Rating Curve= 0 ,0
Exp/Cntr=0.3,0.1

Type RM Length L Ch R = 1 ,23064.7 ,342.7,322.6,304.1
XS GIS Cut Line= 3
     1699937.388      383987.842     1700001.637      384387.188
     1700049.752      384843.594
#Sta/Elev= 30
       0  951.87    39.7  952.96    67.4   951.8    95.2  942.64   126.9   941.2
   142.8   932.6   150.7  930.22   206.2   928.1   285.5  921.08   392.6  917.28
   400.5  916.18   404.5  916.59   408.5  918.78   416.4  923.09   460.4   925.5
   464.3  927.07   480.3  937.91   496.3  941.16   504.2   947.1   512.2  951.22
   544.2  961.83     608  985.97     628  988.52   691.8  992.84   719.8  998.33
   751.7  997.97   767.6  999.95   787.6 1005.87   819.5 1019.36   863.4 1034.38
#Mann= 3 , 0 , 0
       0     .08       0   392.6    .045       0   408.5     .08       0
Bank Sta=392.6,408.5
XS Rating Curve= 0 ,0
Exp/Cntr=0.3,0.1

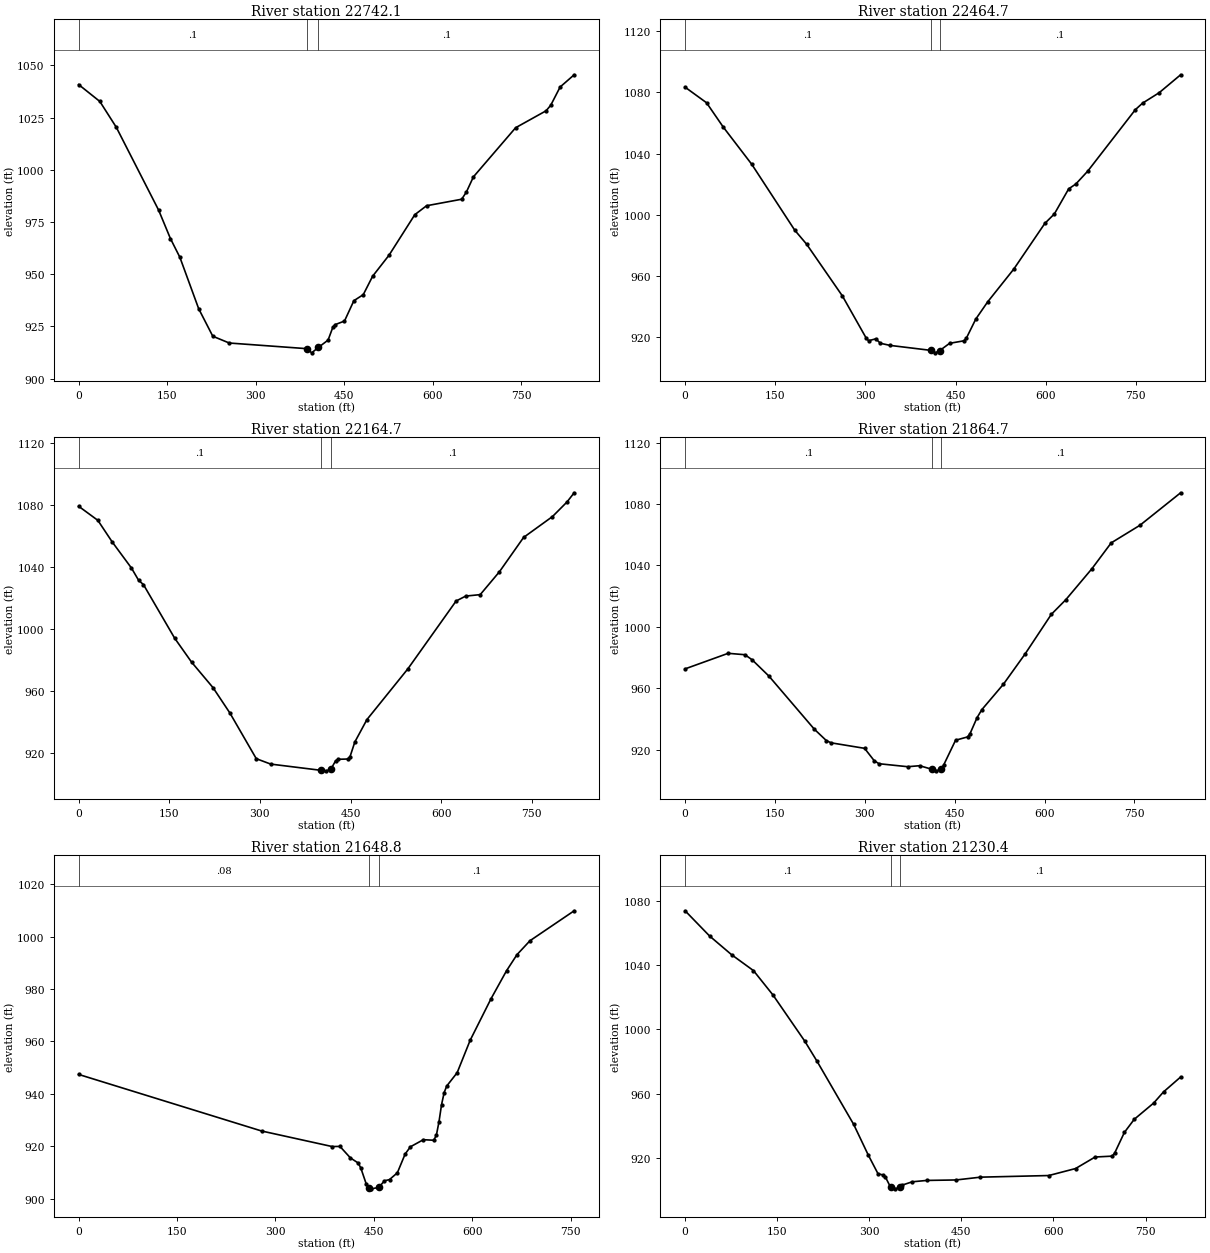
Type RM Length L Ch R = 1 ,22742.1 ,281.6,277.4,264.8
XS GIS Cut Line= 3
      1699463.39      384217.464     1699724.275      384519.129
     1699971.202       384884.13
#Sta/Elev= 30
       0 1040.77    35.9 1032.69    63.8 1020.33   135.6  980.62   155.5  967.06
   171.5  958.11   203.4  933.46   227.3   920.3   255.2  917.06   386.9  914.35
   394.8  912.36   406.3  914.98   422.6  918.46   430.6  924.56   434.6  925.87
   450.4  927.58   466.3  937.32   482.2  940.21   498.1  949.05   525.9  959.11
   569.5  978.48   589.4  982.76   648.9  985.88   656.9  989.32   668.8  996.59
   740.3  1020.1   791.9 1028.21   799.8 1030.86   815.7  1039.6   839.5 1045.45
#Mann= 3 , 0 , 0
       0      .1       0   386.9    .045       0   406.3      .1       0
Bank Sta=386.9,406.3
XS Rating Curve= 0 ,0
Exp/Cntr=0.3,0.1

Type RM Length L Ch R = 1 ,22464.7 ,285.1,300,315
XS GIS Cut Line= 3
     1699251.359      384455.048     1699557.145      384737.511
     1699881.924      384984.958
#Sta/Elev= 30
       0 1083.31    35.7 1073.15    63.4 1057.33     111 1032.94   182.4  990.01
   202.2  980.84   261.7  947.09   301.3  919.59   305.3  917.83   317.2  919.07
   325.1  916.16     341  914.79   408.8  911.55   416.3  909.93   423.8  911.43
   440.1  916.14   463.8  917.77   467.8  919.32   483.7  931.96   503.5  943.21
   547.1  964.67   598.6  994.39   614.5  1000.6   638.3 1016.96   650.2 1020.11
     670 1028.52   749.3 1068.66   761.2 1072.88   788.9 1079.71   824.6 1091.41
#Mann= 3 , 0 , 0
       0      .1       0   408.8    .045       0   423.8      .1       0
Bank Sta=408.8,423.8
XS Rating Curve= 0 ,0
Exp/Cntr=0.3,0.1

Type RM Length L Ch R = 1 ,22164.7 ,318,300,284.1
XS GIS Cut Line= 3
     1699136.968      384529.045     1699307.929      384900.886
     1699511.088      385258.004
#Sta/Elev= 30
       0 1079.41    31.8  1070.3    55.6 1056.32    87.4 1039.48    99.3 1031.53
   107.3 1028.75   158.9  994.13   186.8   978.7   222.5   962.1   250.3  945.78
     294  916.23   317.9  912.73   401.8  908.67   409.3  908.37   417.2  909.26
   425.2  914.81   429.2  915.83   445.2  916.01   449.2  917.58   457.1  927.02
   477.1  941.49   544.9  974.32   624.7 1018.15   640.6 1021.34   664.6 1022.28
   696.5 1037.11   736.4 1059.26   784.2 1072.75   808.2 1082.16   820.1 1088.12
#Mann= 3 , 0 , 0
       0      .1       0   401.8    .045       0   417.2      .1       0
Bank Sta=401.8,417.2
XS Rating Curve= 0 ,0
Exp/Cntr=0.3,0.1

Type RM Length L Ch R = 1 ,21864.7 ,204.5,215.9,230
XS GIS Cut Line= 3
     1698768.476      384845.012     1699099.918      385102.164
      1699428.74       385343.23
#Sta/Elev= 30
       0  972.68    71.9  982.81    99.9  981.89   111.9  978.59   139.8  968.03
   215.7   933.4   235.7  926.01   243.7  924.52   299.6  920.94   315.6  912.92
   323.6  910.92   371.6  908.97   391.5  909.62     412   907.3   419.5  906.28
     427  907.33   431.5  909.98   451.5  926.21   471.5  928.37   475.5  930.37
   487.4  940.94   495.4  946.15   531.4   962.7   567.4   982.3   611.4 1008.21
   635.4 1017.66   679.3    1038   711.3 1054.73   759.3  1066.2   827.2 1087.35
#Mann= 3 , 0 , 0
       0      .1       0     412    .045       0     427      .1       0
Bank Sta=412,427
XS Rating Curve= 0 ,0
Exp/Cntr=0.3,0.1

Type RM Length L Ch R = 1 ,21648.8 ,437.9,418.4,396.9
XS GIS Cut Line= 3
     1698697.955      384891.787     1698955.178      385261.316
     1699119.206      385518.787
#Sta/Elev= 30
       0  947.42   278.9  925.82   386.5  919.88   398.4  919.93   414.4  915.53
   426.3  913.58   430.3  911.62   438.3  905.73   442.7  903.95   446.3  903.73
   457.7  904.28   466.1  906.77     474  907.28   485.9  909.84   497.8  917.02
   505.8  919.78   525.6   922.5   541.4  922.28   545.4   924.2   549.4  929.34
   553.3  935.88   557.3  940.51   561.2  942.99   577.1  948.08   596.9  960.45
   628.6  976.26   652.4  987.02   668.3  993.15   688.1  998.47   755.5 1009.91
#Mann= 3 , 0 , 0
       0     .08       0   442.7    .045       0   457.7      .1       0
Bank Sta=442.7,457.7
XS Rating Curve= 0 ,0
Exp/Cntr=0.3,0.1

Type RM Length L Ch R = 1 ,21230.4 ,294.7,290.4,287
XS GIS Cut Line= 4
      1698270.79      385241.317      1698579.92      385387.866
     1698881.707      385530.029     1699012.977      385536.456
#Sta/Elev= 30
       0 1074.09    39.8 1058.38    75.6 1046.71   111.4 1036.74   143.2  1021.5
   194.9  992.74   214.8  980.24   274.5  940.83   298.4   921.6   314.3   909.9
   322.2  909.27   326.2  907.96   334.6  901.62   342.1  900.56   349.6  901.49
     354  902.94   369.9  904.95   393.7  905.81   441.4   906.1   481.1  907.85
   592.3  908.86     636  913.23   667.8  920.42   695.6  920.97   699.6  922.85
   715.5  935.78   731.5  943.94   763.3  954.14   779.2  961.05   807.1  970.36
#Mann= 3 , 0 , 0
       0      .1       0   334.6    .045       0   349.6      .1       0
Bank Sta=334.6,349.6
XS Rating Curve= 0 ,0
Exp/Cntr=0.3,0.1

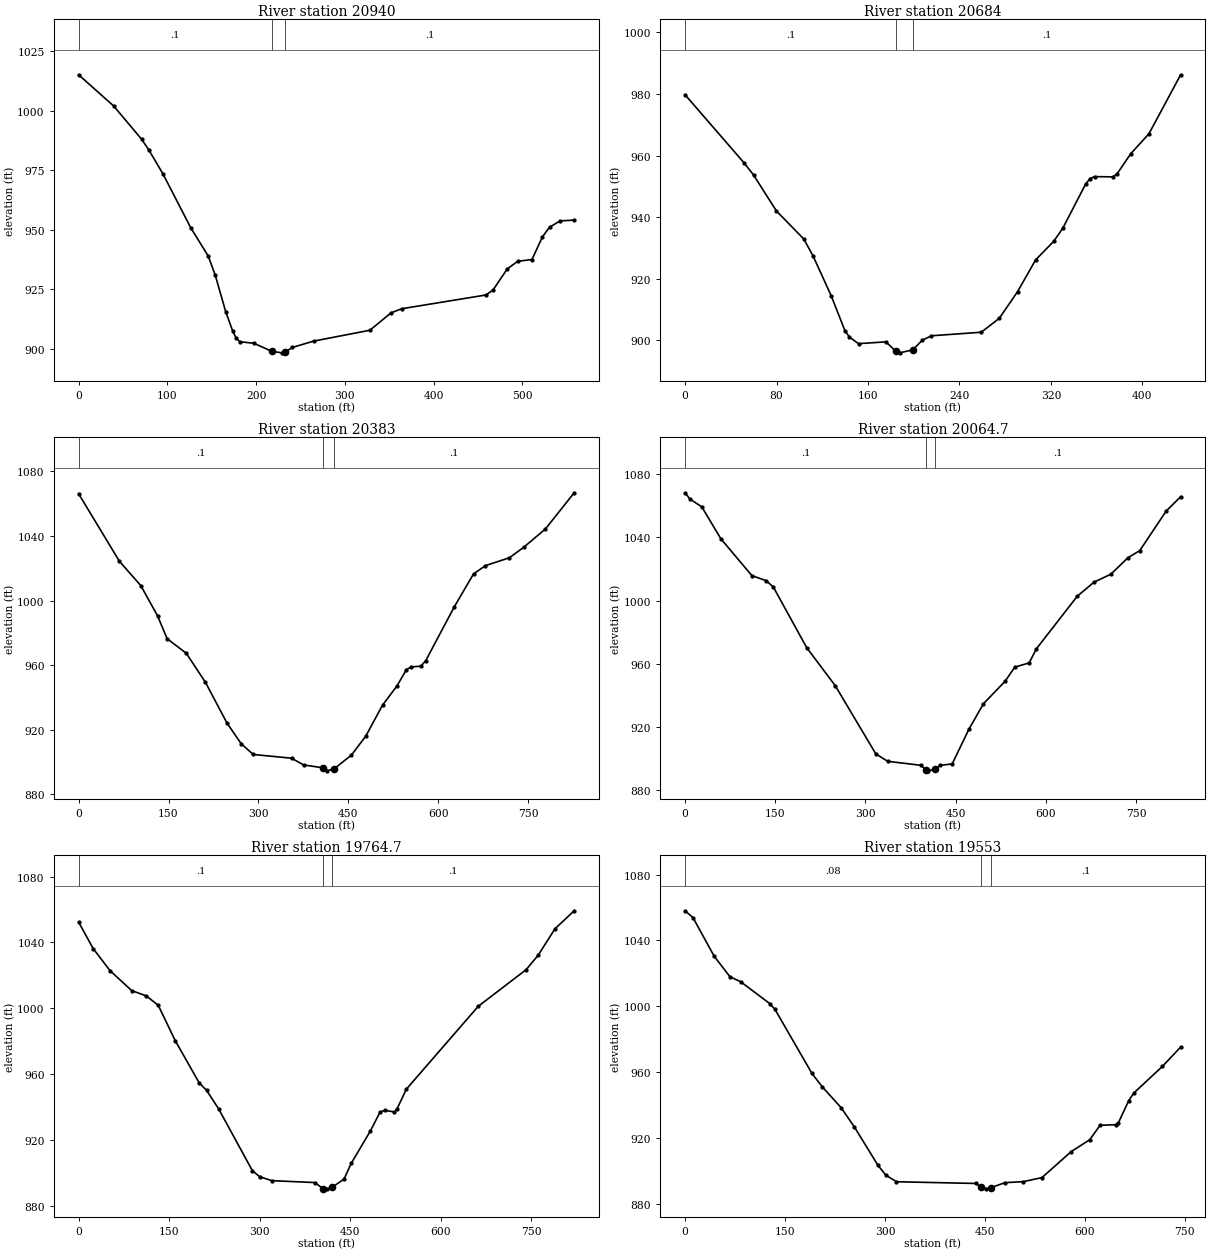
Type RM Length L Ch R = 1 ,20940   ,251.1,256,261.8
XS GIS Cut Line= 3
     1698266.243      385587.018     1698479.483      385658.886
     1698792.708      385773.001
#Sta/Elev= 30
       0 1015.01    39.5 1001.89    71.1  987.87      79   983.5    94.8  973.53
   126.3  950.77   146.1   938.8     154  930.76   165.8  915.39   173.7  907.25
   177.6  904.38   181.6  902.86   197.4  902.21   217.5  898.86     229  898.19
   232.5  898.44   240.9  900.46   264.7  903.11   328.2  907.68     352  914.98
   363.9  916.71   459.2  922.51   467.1  924.67     483  933.46   494.9  936.67
   510.8  937.38   522.7  946.95   530.6  950.95   542.5  953.62   558.4  953.95
#Mann= 3 , 0 , 0
       0      .1       0   217.5    .045       0   232.5      .1       0
Bank Sta=217.5,232.5
XS Rating Curve= 0 ,0
Exp/Cntr=0.3,0.1

Type RM Length L Ch R = 1 ,20684   ,290.5,301,306
XS GIS Cut Line= 3
     1698218.707      385816.404     1698392.848      385896.482
     1698606.076      386010.631
#Sta/Elev= 30
       0  979.72    51.9  957.48    59.9  953.66    79.9  941.99   103.8   932.9
   111.8  927.49   127.8  914.47   139.8  903.13   143.8  901.04   151.7   898.9
   175.7  899.49   184.2  896.48   187.7  895.92   199.2   896.9   207.5  900.02
   215.5  901.46   259.1  902.61   274.9  907.15   290.8  915.76   306.6  926.09
   322.5  932.15   330.4  936.38   350.3  950.67   354.2  952.51   358.2  953.15
   374.1  953.06     378  954.11   389.9  960.61   405.8  967.08   433.5  986.22
#Mann= 3 , 0 , 0
       0      .1       0   184.2    .045       0   199.2      .1       0
Bank Sta=184.2,199.2
XS Rating Curve= 0 ,0
Exp/Cntr=0.3,0.1

Type RM Length L Ch R = 1 ,20383   ,393.8,318.3,324.9
XS GIS Cut Line= 3
     1697947.391      385881.281     1698261.938      386158.424
     1698587.538      386403.847
#Sta/Elev= 30
       0 1066.17    67.9 1024.44   103.8 1009.25   131.8  990.45   147.7  976.39
   179.7  967.35   211.6  949.39   247.5   924.2   271.5  911.22   291.5  904.67
   355.3  902.37   375.3  898.22   407.2  896.45   415.2  894.54   426.7  895.88
   455.2  904.26   479.2  916.05   507.2  935.24   531.2  947.09   547.1  957.28
   555.1  958.93   571.1  959.38   579.1  962.69   627.1  996.26   659.1 1016.57
     679 1021.66     719 1026.55     743 1033.08     779 1044.36     827 1066.78
#Mann= 3 , 0 , 0
       0      .1       0   407.2    .045       0   426.7      .1       0
Bank Sta=407.2,426.7
XS Rating Curve= 0 ,0
Exp/Cntr=0.3,0.1

Type RM Length L Ch R = 1 ,20064.7 ,286.5,300,314.3
XS GIS Cut Line= 3
      1697751.76      386060.781      1698030.84      386358.752
     1698312.412      386664.791
#Sta/Elev= 30
       0 1068.34     7.9 1064.45    27.8  1059.4    59.4 1039.23     111 1015.86
   134.8 1012.64   146.7 1008.65   202.2   970.2   249.7  946.09   317.1  902.92
   336.9  898.16   392.4  895.62   400.8   892.6   404.3  892.12   415.8  893.26
   424.2  895.58   444.2  896.52   472.2  918.66   496.2  934.66   532.2  948.89
   548.2  957.83   572.2  960.53   584.2  969.46   652.2 1002.78   680.2 1011.74
   708.2 1016.77   736.2  1027.1   756.1 1031.68   800.1 1056.77   824.1 1065.85
#Mann= 3 , 0 , 0
       0      .1       0   400.8    .045       0   415.8      .1       0
Bank Sta=400.8,415.8
XS Rating Curve= 0 ,0
Exp/Cntr=0.3,0.1

Type RM Length L Ch R = 1 ,19764.7 ,197.6,211.8,222.1
XS GIS Cut Line= 3
     1697625.496      386147.713     1697788.117      386526.007
     1697933.007      386908.604
#Sta/Elev= 30
       0 1052.39      24  1036.3      52 1022.84      88 1010.69   111.9 1007.53
   131.9 1001.77   159.9  980.36   199.9   954.5   211.9  950.08   231.9  938.84
   287.8  901.23   299.8  897.59   319.8  895.16   391.8  893.99   404.3  890.33
   411.8  890.18   419.3  891.01   439.6  896.05   451.5  905.63   483.3  925.34
   499.2  936.78   507.1   937.9     523  936.95     527  938.42   542.8  950.73
     662 1001.17   741.4 1023.46   761.3 1032.25   789.1 1048.29   820.9 1059.24
#Mann= 3 , 0 , 0
       0      .1       0   404.3    .045       0   419.3      .1       0
Bank Sta=404.3,419.3
XS Rating Curve= 0 ,0
Exp/Cntr=0.3,0.1

Type RM Length L Ch R = 1 ,19553   ,141.9,131,122.1
XS GIS Cut Line= 4
     1697580.143      386139.339     1697591.755      386591.306
     1697603.951      386745.997     1697698.958      386843.965
#Sta/Elev= 30
       0 1058.01    11.9 1053.82    43.6 1030.43    67.4 1017.92    83.3 1014.93
   126.9 1001.67   134.8  998.17   190.4  959.19   206.2   950.9     234  938.46
   253.8  926.86   289.5  903.35   301.4  897.35   317.3  893.37   436.2  892.33
   444.6  890.15   452.1  889.06   459.6  889.85     480   892.8   507.8  893.45
   535.7   895.9   579.4  911.66   607.3  918.86   622.9  927.69   646.3  928.02
   650.2  929.04   665.8  942.61   673.6  947.33   716.5  963.48   743.8   975.2
#Mann= 3 , 0 , 0
       0     .08       0   444.6    .045       0   459.6      .1       0
Bank Sta=444.6,459.6
XS Rating Curve= 0 ,0
Exp/Cntr=0.3,0.1

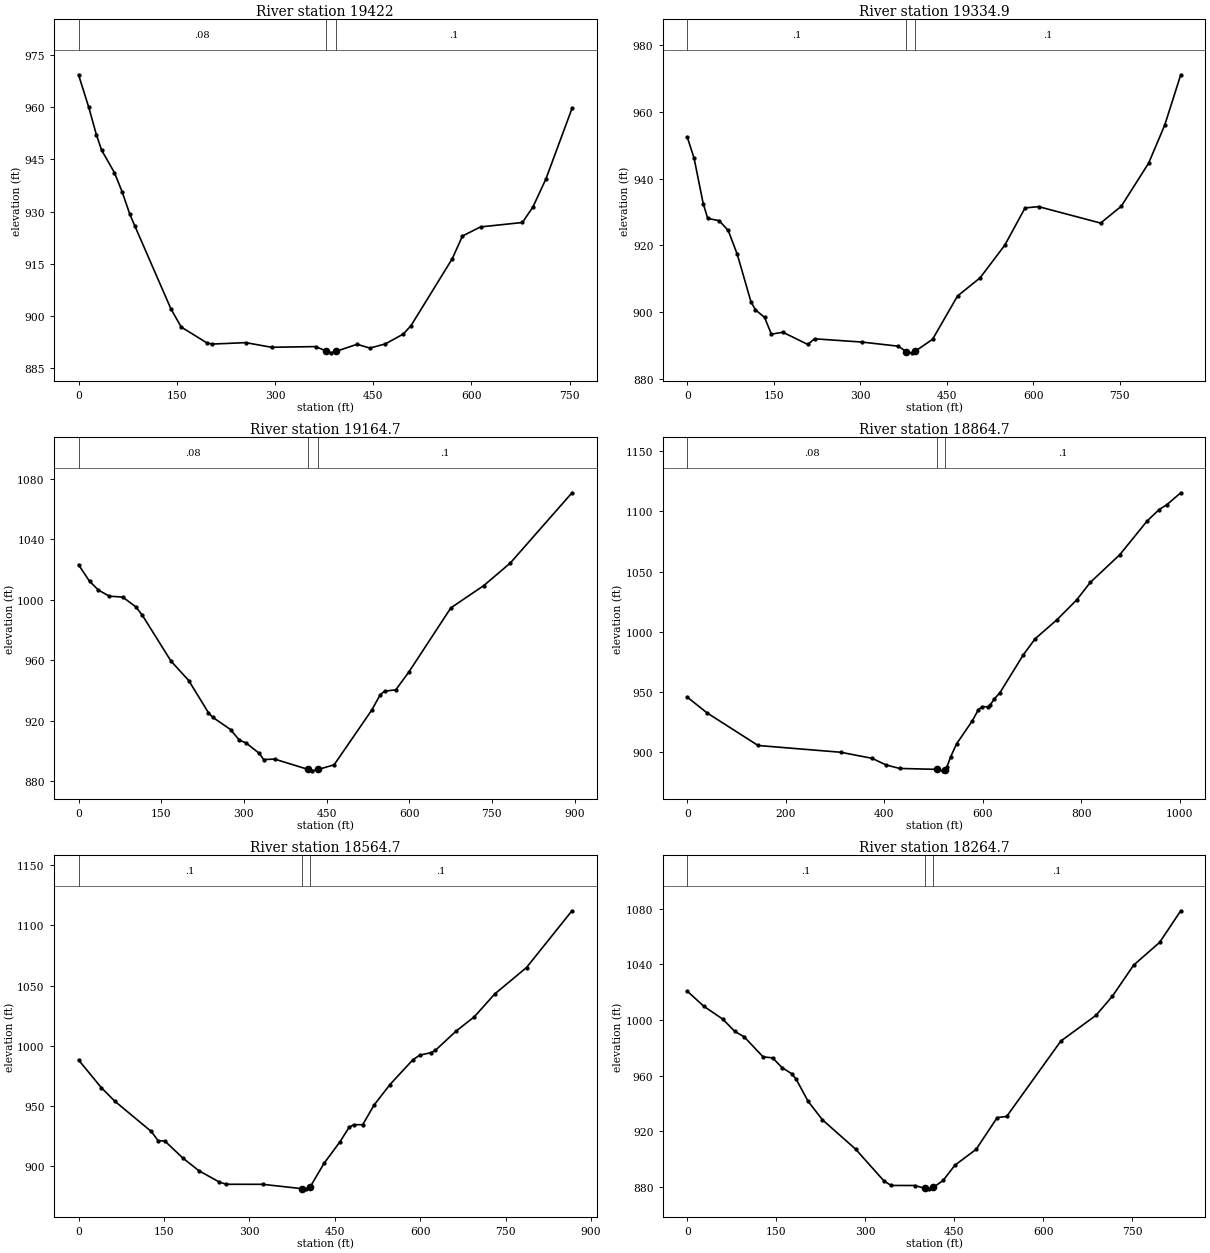
Type RM Length L Ch R = 1 ,19422   ,92.3,87.1,81.6
XS GIS Cut Line= 6
     1697364.757      386248.262     1697358.247      386440.319
     1697425.521      386481.551     1697474.349      386628.036
     1697552.474      386790.796     1697664.236      386887.367
#Sta/Elev= 30
       0  969.29    15.7   959.9    27.4  951.98    35.3  947.62    54.9  941.16
    66.7  935.63    78.4  929.19    86.3  925.74   141.2  902.01   156.9  896.82
   196.1  892.27     204  891.94   255.3  892.35   294.8  891.02   362.1  891.21
     378  889.97   385.9  889.42     393  889.83   425.5  891.88   445.1  890.78
   468.6  891.99   496.1  894.82   507.9  897.26   570.7  916.42   586.4  922.98
     614  925.59   677.9  926.86   693.8  931.24   713.8  939.34   753.7  959.62
#Mann= 3 , 0 , 0
       0     .08       0     378    .045       0     393      .1       0
Bank Sta=378,393
XS Rating Curve= 0 ,0
Exp/Cntr=0.3,0.1

Type RM Length L Ch R = 1 ,19334.9 ,150.1,170.2,189.9
XS GIS Cut Line= 6
     1697269.271      386254.772     1697255.165      386443.574
     1697371.267      386501.083     1697397.309      386648.652
     1697544.878      386832.029     1697532.943      386978.513
#Sta/Elev= 30
       0  952.48    11.8  946.15    27.6  932.56    35.5  928.08    55.2  927.42
      71  924.49    86.8  917.27   110.4  903.11   118.3  900.65   134.1  898.39
   145.9  893.36   165.7  893.95     209  890.29   220.7  891.98   303.2     891
   366.2  889.76   380.1  888.09   389.9  887.77   395.1  888.22   425.4  891.83
   468.7  904.82   507.8  910.26   550.7  920.07   585.8  931.24   609.3  931.62
   716.8  926.69   752.6  931.72   800.2  944.69     828  956.06   855.8  971.17
#Mann= 3 , 0 , 0
       0      .1       0   380.1    .045       0   395.1      .1       0
Bank Sta=380.1,395.1
XS Rating Curve= 0 ,0
Exp/Cntr=0.3,0.1

Type RM Length L Ch R = 1 ,19164.7 ,319.3,300,283.3
XS GIS Cut Line= 3
     1697257.661      386059.912     1697236.613      386487.107
     1697218.184      386954.291
#Sta/Elev= 30
       0 1023.28      20 1012.29      36 1006.51      56 1002.41      80 1001.88
   103.9  995.39   115.9  989.73   167.9  959.39   199.9  946.59   235.8   925.2
   243.8  922.14   275.8  914.12   291.8  907.08   303.8  905.27   327.8  898.39
   335.8  894.22   355.8  894.54   415.7  887.79   423.7  886.76   435.2  887.72
   463.7  890.76   531.6  926.79   547.6  937.29   555.6  939.53   575.6  940.42
   599.6  952.38   675.5  994.69   735.4  1009.5   783.4 1024.41   895.3 1070.92
#Mann= 3 , 0 , 0
       0     .08       0   415.7    .045       0   435.2      .1       0
Bank Sta=415.7,435.2
XS Rating Curve= 0 ,0
Exp/Cntr=0.3,0.1

Type RM Length L Ch R = 1 ,18864.7 ,314.9,300,283.1
XS GIS Cut Line= 3
     1696726.411      386050.797     1696955.607      386512.193
     1697139.146      386963.531
#Sta/Elev= 30
       0  945.86    39.9  932.86   143.8  905.72   311.5  900.11   375.4  895.07
   403.4  889.62   431.3  886.67   507.7   885.9   519.2  884.68   522.7  885.23
   527.2  887.71   535.2  896.47   547.1   907.1   579.1  926.24   591.1  935.24
     599  937.97     611  937.82     615  939.02     623  944.08     635  949.46
   682.9  981.15   706.9  994.41   750.8 1010.01   790.8 1026.44   818.7 1041.07
   878.6 1064.08   934.5 1092.22   958.5 1101.52   974.5 1105.69  1002.4 1115.46
#Mann= 3 , 0 , 0
       0     .08       0   507.7    .045       0   522.7      .1       0
Bank Sta=507.7,522.7
XS Rating Curve= 0 ,0
Exp/Cntr=0.3,0.1

Type RM Length L Ch R = 1 ,18564.7 ,316.9,300,282.3
XS GIS Cut Line= 3
     1696424.847       386439.93     1696727.643      386700.146
     1697073.481      387014.868
#Sta/Elev= 30
       0  988.13    39.9  965.13    63.9  953.73   127.8  928.63   139.7  921.01
   151.7  920.64   183.6  906.39   211.6  895.93   247.5  886.53   259.5  884.71
   323.4  884.68   391.7   881.1   399.2  880.92   406.7  882.35   431.2   902.1
   459.2     920   475.2  932.05   483.2  934.23   499.2  934.29   519.1  950.57
   547.1  967.68   587.1  988.14   599.1  992.04   619.1  994.18     627  996.14
     663 1012.03     695 1023.88     731 1042.93   786.9 1064.95   866.8 1112.14
#Mann= 3 , 0 , 0
       0      .1       0   391.7    .045       0   406.7      .1       0
Bank Sta=391.7,406.7
XS Rating Curve= 0 ,0
Exp/Cntr=0.3,0.1

Type RM Length L Ch R = 1 ,18264.7 ,276.9,263.8,248.1
XS GIS Cut Line= 3
     1696237.133       386870.22     1696630.782      386976.059
     1697039.269      387091.427
#Sta/Elev= 30
       0 1020.73      28 1009.86      60 1000.63    79.9  991.92    95.9  987.96
   127.9  973.56   143.9  972.86   159.8  965.86   175.8  961.57   183.8   957.4
   203.8  941.64   227.8  928.46   283.7   907.4   331.7  884.48   343.7  881.27
   383.6  881.22   400.1   879.3   407.6  878.84   415.1  879.98   431.4  884.83
   451.3  895.81     487  907.15   522.7  930.01   538.5  930.77   629.8  984.86
   689.3 1003.42     717  1017.2   752.8 1039.48   796.4 1055.69   832.1 1078.43
#Mann= 3 , 0 , 0
       0      .1       0   400.1    .045       0   415.1      .1       0
Bank Sta=400.1,415.1
XS Rating Curve= 0 ,0
Exp/Cntr=0.3,0.1

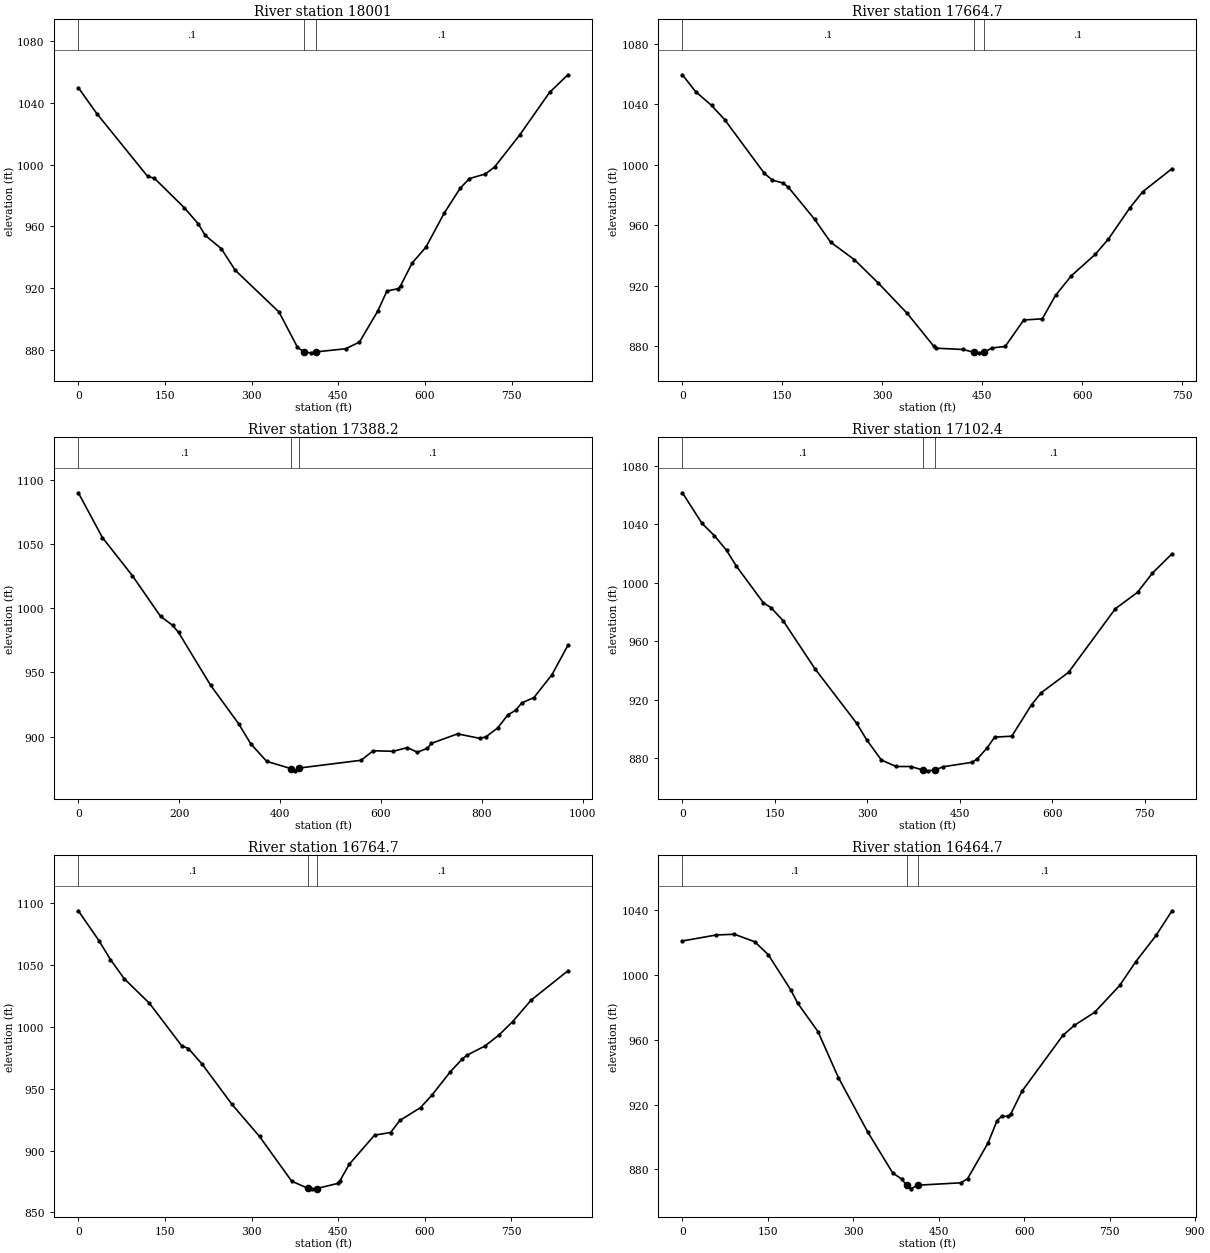
Type RM Length L Ch R = 1 ,18001   ,339.4,336.2,332.5
XS GIS Cut Line= 3
     1696189.952      387270.849      1696591.81      387235.622
     1697032.224       387177.97
#Sta/Elev= 30
       0 1049.91      32 1033.12   119.8  992.52   131.8  991.18   183.7  972.09
   207.7  961.68   219.7  954.23   247.6  945.62   271.6  931.68   347.5  904.57
   379.4  881.77   391.4   878.5   403.4  878.17   410.9  878.77   462.9  880.81
   486.7  885.12   518.4  905.22   534.3  918.25   554.1  919.74   558.1  921.78
   577.9  936.34   601.7  946.57   633.4  968.61   661.2  984.82     677  991.01
   704.8  994.05   720.7  998.55   764.3 1019.34   815.8 1046.82   847.6 1058.26
#Mann= 3 , 0 , 0
       0      .1       0   391.4    .045       0   410.9      .1       0
Bank Sta=391.4,410.9
XS Rating Curve= 0 ,0
Exp/Cntr=0.3,0.1

Type RM Length L Ch R = 1 ,17664.7 ,267.2,276.5,281.9
XS GIS Cut Line= 3
      1696281.21      387590.326     1696720.977      387524.968
     1697003.754      387460.953
#Sta/Elev= 30
       0 1059.35    19.8 1048.22    43.7 1039.12    63.5 1029.65   123.1  994.12
     135  989.75   150.8  987.83   158.8  985.12   198.5  963.76   222.3  948.75
     258  937.18   293.8  921.74   337.4   901.6   377.1  879.98   381.1  878.64
   420.8   877.8   437.1  875.98   444.6  875.58   452.1  875.95   464.5   878.8
   484.3  879.81   512.1  897.28   539.9  898.06   559.8  913.54   583.6  926.53
   619.4  940.66   639.2  950.82     671  971.19   690.8  982.13   734.5  997.29
#Mann= 3 , 0 , 0
       0      .1       0   437.1    .045       0   452.1      .1       0
Bank Sta=437.1,452.1
XS Rating Curve= 0 ,0
Exp/Cntr=0.3,0.1

Type RM Length L Ch R = 1 ,17388.2 ,275.3,285.8,298.7
XS GIS Cut Line= 4
     1696294.344      387752.809     1696722.886      387773.816
     1697097.387      387765.451      1697140.82      387604.356
#Sta/Elev= 30
       0 1089.76    47.7 1054.96   107.3  1025.2   162.9  993.69   186.7  986.73
   198.6  981.15   262.2  940.07   317.8   910.1   341.7  894.57   373.4  880.88
   421.6   875.2   429.1  873.49   436.6  875.62   560.6  881.71   584.5   889.1
   624.3  888.69   652.2  891.58   672.1  887.95   692.1  891.07     700  894.89
   751.8  902.25   795.7  898.77   807.6  899.87   831.5  906.92   851.3  916.96
   867.2  920.66   879.1  926.36     903  930.43   938.7  948.14   970.5   971.1
#Mann= 3 , 0 , 0
       0      .1       0   421.6    .045       0   436.6      .1       0
Bank Sta=421.6,436.6
XS Rating Curve= 0 ,0
Exp/Cntr=0.3,0.1

Type RM Length L Ch R = 1 ,17102.4 ,302.7,337.6,333.8
XS GIS Cut Line= 3
     1696263.411      387919.268     1696656.968      388020.379
     1697031.641      388120.006
#Sta/Elev= 30
       0 1061.48    31.9 1040.49    51.8 1032.19    71.7 1022.01    87.6 1011.24
   131.5   986.1   143.4  982.97   163.3  973.97   215.1  940.98   282.8  903.64
   298.8  892.45   322.7  878.61   346.6  874.17   370.5  874.15   390.4  871.71
   398.4   871.2   410.3  871.85   422.3  873.96   470.3  877.07   478.3  879.39
   494.3  886.92   506.3  894.26   534.2  894.91   566.2  916.41   582.2  924.76
   626.2  938.58   702.1  982.12   738.1  993.34     762 1006.37     794 1019.71
#Mann= 3 , 0 , 0
       0      .1       0   390.4    .045       0   410.3      .1       0
Bank Sta=390.4,410.3
XS Rating Curve= 0 ,0
Exp/Cntr=0.3,0.1

Type RM Length L Ch R = 1 ,16764.7 ,300.1,300,294.7
XS GIS Cut Line= 3
     1696123.731       388042.38     1696486.234       388223.44
     1696869.198      388445.312
#Sta/Elev= 30
       0 1093.38    35.8 1069.22    55.6 1054.07    79.4 1038.62   123.2 1018.72
   178.8   984.6   190.7  982.21   214.5  969.61   266.2  937.14   313.8  911.34
   369.4  875.29   397.7  869.47   405.2  869.08   412.7  869.29   449.1  873.44
     453  875.54     469  888.82   512.9  912.38   540.8  914.52   556.7  924.22
   592.6  934.62   612.6  944.82   644.4  963.62   664.4  973.61   672.4  976.69
   704.2  984.32   728.2  993.06   752.1 1003.95     784 1021.26   847.8 1044.94
#Mann= 3 , 0 , 0
       0      .1       0   397.7    .045       0   412.7      .1       0
Bank Sta=397.7,412.7
XS Rating Curve= 0 ,0
Exp/Cntr=0.3,0.1

Type RM Length L Ch R = 1 ,16464.7 ,296.7,300,303.5
XS GIS Cut Line= 3
     1695971.077      388289.412     1696340.739      388444.432
     1696762.401      388624.533
#Sta/Elev= 30
       0 1021.05    59.5 1024.75    91.3  1025.2     127 1020.55   150.8 1012.56
   190.5  990.65   202.4  982.59   238.1     965   273.8  936.66   325.4  902.98
   369.1  877.75     385  873.94   393.4  870.13   400.8   867.9   412.8  870.15
   488.6  871.62   500.5   874.1   536.4  896.15   552.4  910.08   560.3  912.68
   572.3  912.73   576.3  914.05   596.2  928.28     668  962.73   687.9  968.87
   723.8  977.01   767.7   993.6   795.6 1008.13   831.5 1024.46   859.4  1039.7
#Mann= 3 , 0 , 0
       0      .1       0   393.4    .045       0   412.8      .1       0
Bank Sta=393.4,412.8
XS Rating Curve= 0 ,0
Exp/Cntr=0.3,0.1