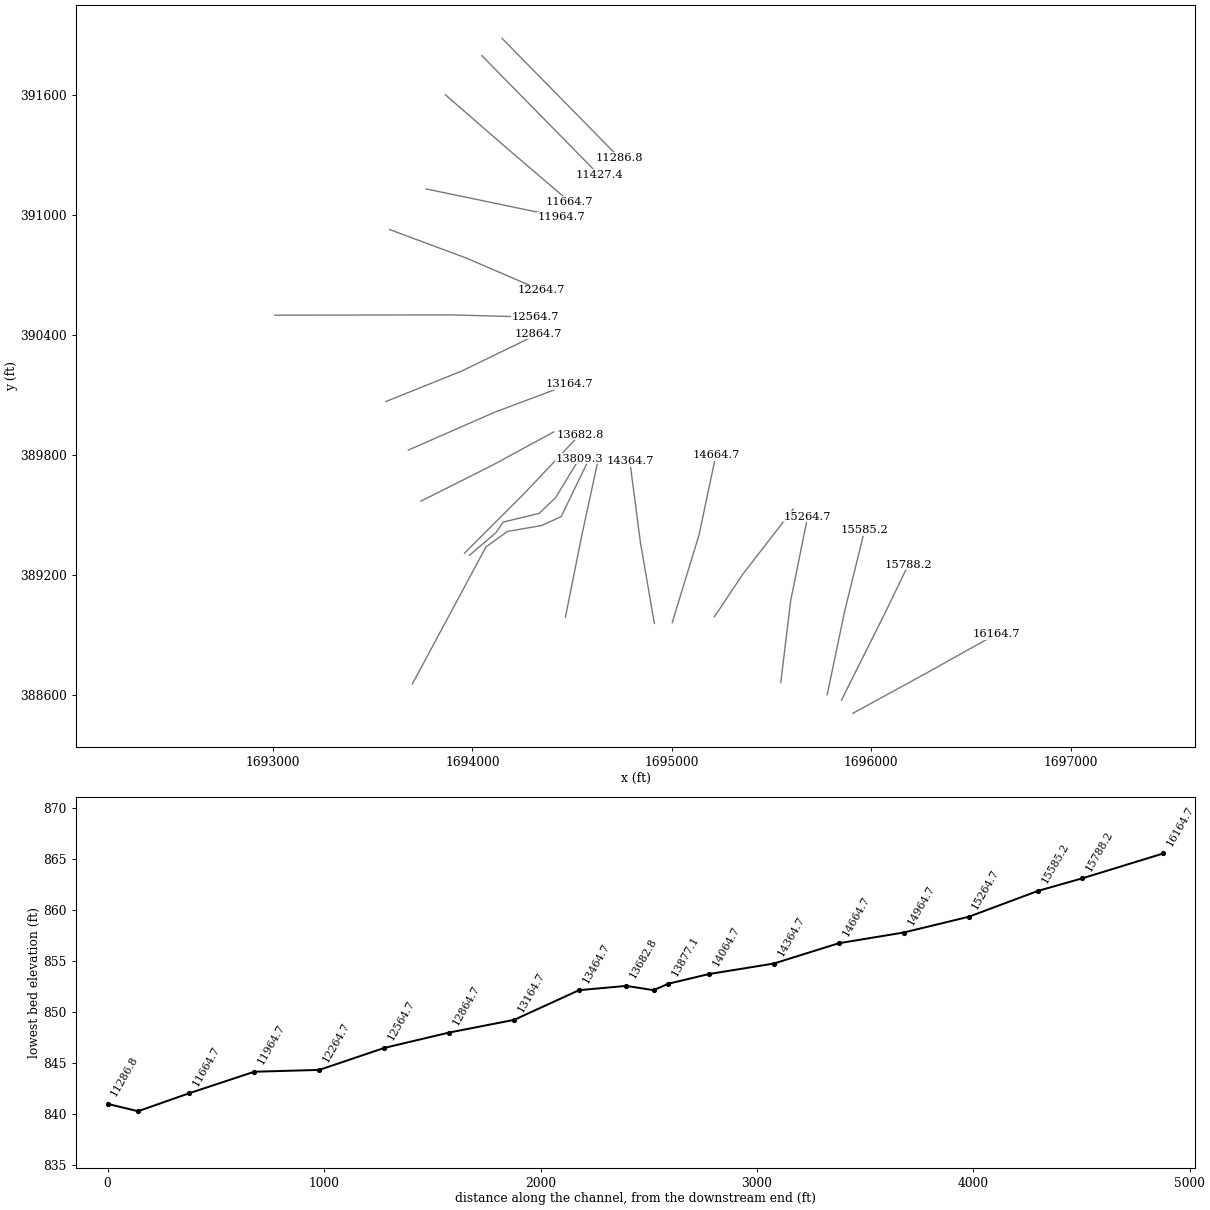
HEC-RAS study MUDRV.prj: MUDRV

--- MUDRV.g01 (geometry) --- (continued)

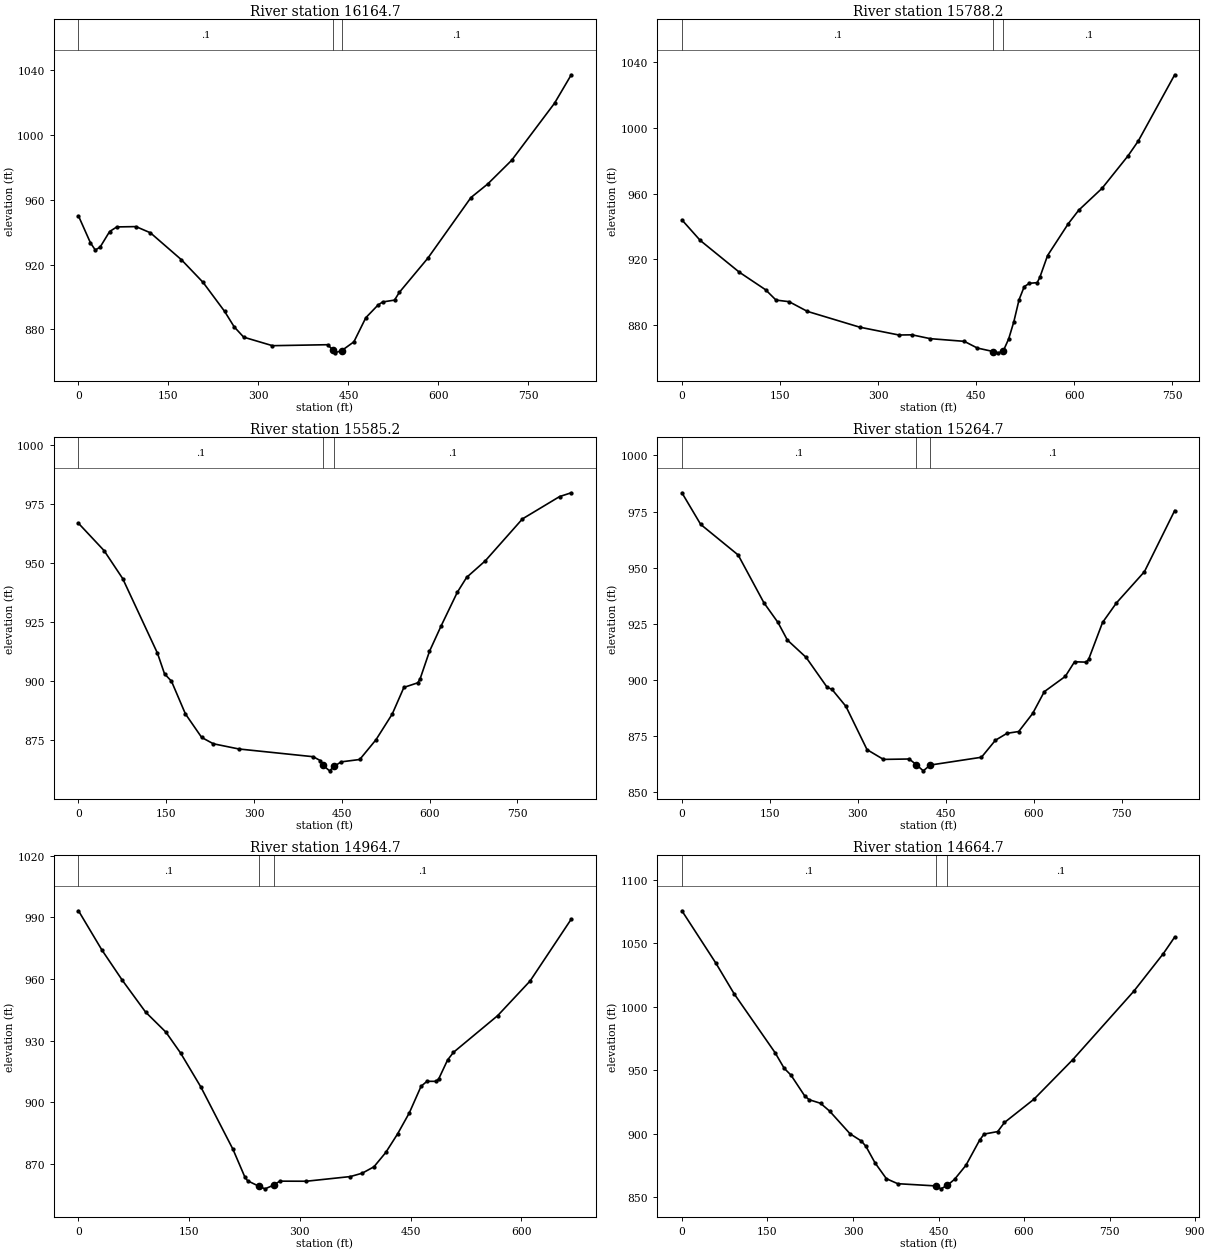
Type RM Length L Ch R = 1 ,16164.7 ,348.9,376.5,401.3
XS GIS Cut Line= 3
     1695907.311      388510.606     1696285.993      388716.684
     1696626.931      388906.439
#Sta/Elev= 30
       0  949.94      20  933.32    27.9     929    35.9  930.65    51.9  940.35
    63.9  943.18    95.8  943.38   119.8  939.57   171.6  922.94   207.6  909.02
   243.5  891.14   259.5  881.58   275.4  875.22   323.3  869.98   415.2  870.58
   423.6   867.5   427.1  865.57   438.6  866.92     459  872.35   478.9  887.23
   498.8  894.88   506.8  896.92   526.7  898.07   534.6  902.78   582.4  923.99
   654.1  961.29     682  969.63   721.8  984.19   793.4 1019.42   821.3 1036.96
#Mann= 3 , 0 , 0
       0      .1       0   423.6    .045       0   438.6      .1       0
Bank Sta=423.6,438.6
XS Rating Curve= 0 ,0
Exp/Cntr=0.3,0.1

Type RM Length L Ch R = 1 ,15788.2 ,194.9,203,211.3
XS GIS Cut Line= 3
     1695850.823      388577.005     1696068.025       389009.32
     1696185.959      389251.925
#Sta/Elev= 30
       0  944.05      28  931.54      88  912.14     128   901.5   143.9  895.23
   163.9  894.26   191.9  888.35   271.9  878.74   331.9  873.97   351.9  874.08
   379.8  871.75   431.8  870.12   451.8  866.04   476.3  863.89   483.8  863.12
   491.3  864.15   499.7  871.57   507.6  882.04   515.6  895.45   523.5  903.41
   531.4  905.44   543.3  905.84   547.3  909.01   559.2  922.34   590.9  941.74
   606.8  949.92   642.5  963.25   682.2     983     698   992.1   753.6 1032.36
#Mann= 3 , 0 , 0
       0      .1       0   476.3    .045       0   491.3      .1       0
Bank Sta=476.3,491.3
XS Rating Curve= 0 ,0
Exp/Cntr=0.3,0.1

Type RM Length L Ch R = 1 ,15585.2 ,311.5,320.4,321.8
XS GIS Cut Line= 3
     1695779.121      388603.154     1695866.324      389019.083
     1695966.439      389424.032
#Sta/Elev= 30
       0  966.85    43.7  955.28    75.5  943.43     135  911.75     147  903.04
   158.9   899.9   182.7  886.05   210.5  876.06   230.4  873.38     274  871.17
   401.1  867.89   413.1  866.26   417.5  864.36     429   861.9   436.9  863.79
   448.8   865.7   480.6  866.71   508.4  875.09   536.2     886   556.1  897.28
   579.9  899.23   583.9  900.98   599.8  912.56   619.6  923.29   647.4  937.62
   663.3  943.92   695.1  950.92   758.7  968.72   822.2  978.19   842.1  979.79
#Mann= 3 , 0 , 0
       0      .1       0   417.5    .045       0   436.9      .1       0
Bank Sta=417.5,436.9
XS Rating Curve= 0 ,0
Exp/Cntr=0.3,0.1

Type RM Length L Ch R = 1 ,15264.7 ,317.9,300,282.3
XS GIS Cut Line= 3
     1695546.289      388664.751     1695595.974      389073.198
     1695681.333      389493.273
#Sta/Elev= 30
       0  983.35      32  969.25    95.9  955.61   139.8   934.3   163.8  925.51
   179.8  917.68   211.7  909.96   247.7  896.57   255.7  895.73   279.6  888.12
   315.6  868.81   343.6  864.46   387.5  864.64   399.5  862.13   411.5  859.36
   423.4  861.94   510.7  865.42   534.5  873.01   554.3   876.1   574.2  876.89
     598  884.95   617.8  894.66   653.6  901.47   669.4  907.99   689.3  907.83
   693.3  909.01   717.1  925.51   740.9  934.27   788.5  948.16   840.1  975.41
#Mann= 3 , 0 , 0
       0      .1       0   399.5    .045       0   423.4      .1       0
Bank Sta=399.5,423.4
XS Rating Curve= 0 ,0
Exp/Cntr=0.3,0.1

Type RM Length L Ch R = 1 ,14964.7 ,288.9,300,317
XS GIS Cut Line= 3
     1695213.737      388993.245     1695356.789        389206.5
     1695609.199      389530.909
#Sta/Elev= 30
       0  993.17    31.6  974.15    59.3   959.4    90.9  943.87   118.5  934.08
   138.3  923.96   165.9  907.35   209.4  877.02   225.2  863.78   229.1  861.76
   244.9     859   252.8  857.82   264.3  859.61   272.8  861.56   308.7  861.52
   368.5   863.8   384.5  865.44   400.4  868.55   416.4  875.51   432.4  884.54
   448.3  894.78   464.3  907.76   472.3  910.17   484.3  910.14   488.2  911.36
   500.2  920.56   508.2  924.28   568.1  942.14     612  958.99   667.8  989.12
#Mann= 3 , 0 , 0
       0      .1       0   244.9    .045       0   264.3      .1       0
Bank Sta=244.9,264.3
XS Rating Curve= 0 ,0
Exp/Cntr=0.3,0.1

Type RM Length L Ch R = 1 ,14664.7 ,281.9,300,312.8
XS GIS Cut Line= 3
     1695001.844      388963.653      1695136.41      389401.684
     1695220.681        389798.8
#Sta/Elev= 30
       0 1075.67    59.8 1034.28    91.6 1010.31   163.4  963.96   179.3  951.72
   191.3  946.27   215.2  930.03   223.1  926.94   243.1  924.13     259  917.98
   294.9  900.09   314.8  894.39   322.8  890.15   338.7  877.21   358.6  864.75
   378.5  860.82   446.3  859.04   454.2  856.77   465.7   859.6   478.1  864.25
     498  875.24   521.9  894.93   529.9  899.87   553.8  901.85   565.7     909
   617.4  927.33   685.1  958.29   792.6 1012.39   844.3 1041.97   864.2 1054.98
#Mann= 3 , 0 , 0
       0      .1       0   446.3    .045       0   465.7      .1       0
Bank Sta=446.3,465.7
XS Rating Curve= 0 ,0
Exp/Cntr=0.3,0.1

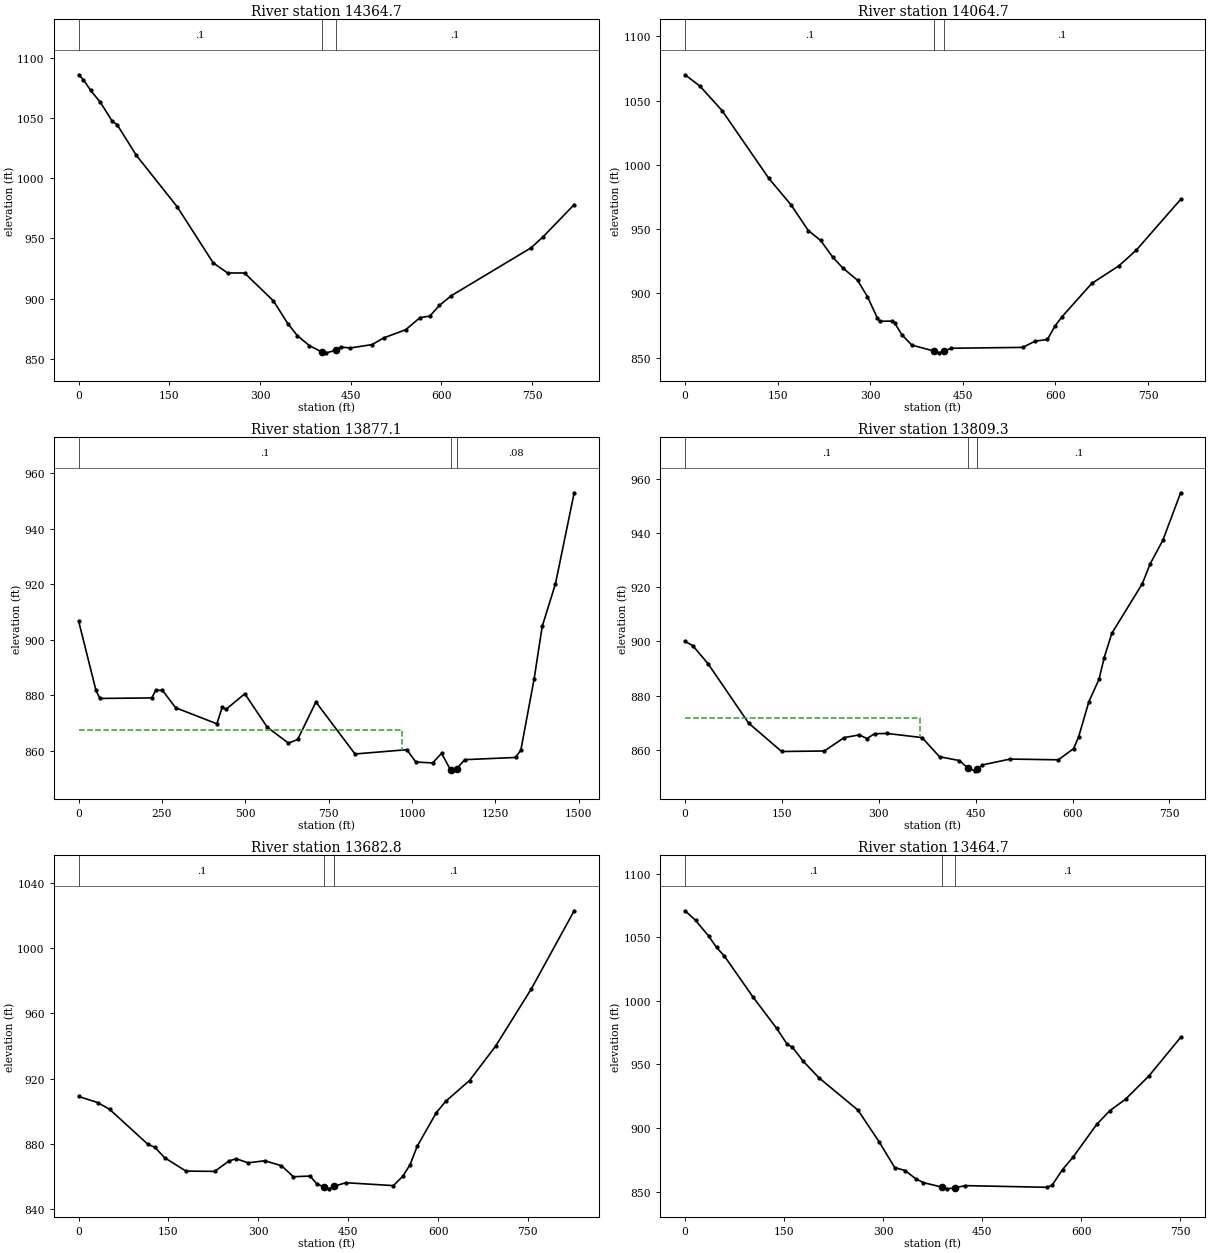
Type RM Length L Ch R = 1 ,14364.7 ,313.8,300,287
XS GIS Cut Line= 3
     1694912.397      388959.729     1694842.472      389363.139
       1694789.2      389769.587
#Sta/Elev= 30
       0 1086.18       8 1082.05    19.9 1073.16    35.8 1063.36    55.6 1047.54
    63.6 1044.68    95.4 1019.17     163  976.31   222.6   929.6   246.4   921.2
   274.3  921.25     322  898.06   345.8  879.19   361.7   869.1   381.6  860.76
   401.9  855.58   409.4  854.78   425.3  856.82   433.3  859.57   449.2  858.85
     485  861.61   504.9  867.32   540.8  874.01   564.6  884.12   580.6  885.31
   596.5  894.24   616.4  902.39   747.7  942.04   767.6  951.13   819.4  978.13
#Mann= 3 , 0 , 0
       0      .1       0   401.9    .045       0   425.3      .1       0
Bank Sta=401.9,425.3
XS Rating Curve= 0 ,0
Exp/Cntr=0.3,0.1

Type RM Length L Ch R = 1 ,14064.7 ,223.5,187.7,152.2
XS GIS Cut Line= 3
     1694466.121      388990.346     1694547.267      389393.444
     1694630.404      389776.231
#Sta/Elev= 30
       0 1070.18      24 1061.38    59.9 1042.33   135.7  989.51   171.7   968.9
   199.6  948.96   219.6  941.21   239.5  928.04   255.5  919.84   279.4  910.24
   295.4   897.5   311.4  881.01   315.4  878.35   335.3  878.44   339.3  877.17
   351.3  867.81   367.3   859.8   403.7  855.08   411.2  853.75   418.7  854.92
   431.2  857.33   547.1  857.99   567.1  862.84   587.1  864.15     599   874.4
     611  882.02     659  907.81     703  921.52     731  933.66   802.9  973.17
#Mann= 3 , 0 , 0
       0      .1       0   403.7    .045       0   418.7      .1       0
Bank Sta=403.7,418.7
XS Rating Curve= 0 ,0
Exp/Cntr=0.3,0.1

Type RM Length L Ch R = 1 ,13877.1 ,65.7,67.8,81.1
XS GIS Cut Line= 6
     1693698.553      388657.738      1694068.04       389341.92
     1694175.738      389418.834     1694346.094      389448.131
     1694444.835      389492.619     1694572.873      389756.291
#Sta/Elev= 30
       0  906.78    51.8  881.89    63.8   878.9   219.3  879.09   231.2  881.83
   251.2  881.84     291  875.54   414.6  869.76   430.6  875.71   442.5  875.02
   498.4  880.59   566.1  868.46   629.3  862.79   656.8   864.1   711.6  877.61
   828.8  858.88   984.2  860.42  1011.3  855.98  1061.4  855.64  1088.4  859.11
  1115.5   853.1  1119.3   852.8  1133.6  853.55    1158  856.83  1310.2  857.62
  1326.2  860.29  1366.2  886.04  1390.2  904.85  1430.1  920.29  1486.1  953.04
#Mann= 3 , 0 , 0
       0      .1       0  1115.5    .045       0  1133.6     .08       0
#XS Ineff= 2 , 0
          969.59  867.43
Permanent Ineff=
       F       F
Bank Sta=1115.5,1133.6
XS Rating Curve= 0 ,0
Exp/Cntr=0.3,0.1

Type RM Length L Ch R = 1 ,13809.3 ,114.6,126.5,127.9
XS GIS Cut Line= 6
     1693984.766      389299.477     1694119.314      389414.494
     1694154.036      389465.492     1694334.158      389508.895
     1694416.623       389587.02     1694535.981      389782.333
#Sta/Elev= 30
       0  900.02    11.8  898.46    35.4  891.82    98.3  869.83   149.5  859.32
   215.6  859.51   246.5  864.48   269.9  865.45   281.6   864.1   293.4  865.89
   312.9  865.99     367  864.46     394  857.38   424.9  855.97   437.5  853.27
   448.4  852.17   452.5  852.75   460.2  854.34   503.2  856.52     578  856.25
   601.6  860.37   609.5  864.78   625.3  877.75   641.1  886.08     649  894.01
   660.8     903   708.2  921.42     720   928.6   739.8  937.39   767.4  954.97
#Mann= 3 , 0 , 0
       0      .1       0   437.5    .045       0   452.5      .1       0
#XS Ineff= 2 , 0
          364.05  871.86
Permanent Ineff=
       F       F
Bank Sta=437.5,452.5
XS Rating Curve= 0 ,0
Exp/Cntr=0.3,0.1

Type RM Length L Ch R = 1 ,13682.8 ,231.3,218.1,204.9
XS GIS Cut Line= 3
     1693960.104      389310.543     1694256.859      389605.257
     1694538.293      389902.012
#Sta/Elev= 30
       0  909.13    31.9  905.38    51.8  901.23   115.5   879.9   127.5  877.96
   143.4  871.69   179.2  863.44     227  863.28   250.9  869.62   262.9  871.03
   282.8  868.51   310.7  869.78   338.6  866.73   358.5     860   386.4  860.42
   398.3   855.3   410.3  853.94   418.2  852.59   426.2  854.12     446  856.34
   525.4  854.56   541.3  860.36   553.2  867.32   565.2  878.67   596.9  899.11
   612.8  906.19   652.5  918.87   696.2  940.02   755.8  975.07   827.2 1022.78
#Mann= 3 , 0 , 0
       0      .1       0   410.3    .045       0   426.2      .1       0
Bank Sta=410.3,426.2
XS Rating Curve= 0 ,0
Exp/Cntr=0.3,0.1

Type RM Length L Ch R = 1 ,13464.7 ,303.2,300,291.8
XS GIS Cut Line= 3
     1693741.854      389570.238      1694096.68      389747.648
     1694407.943      389915.796
#Sta/Elev= 30
       0 1070.74    15.9 1063.18    35.7 1050.85    47.6 1041.92    59.5 1035.12
   103.1 1002.77   138.8  978.23   154.7  965.76   162.6  963.48   178.5  952.73
   202.3  939.65   261.8  914.04   293.6  889.31   317.4  868.94   333.2  866.55
   349.1  860.17     361  857.03   389.2  853.51   396.7  852.17   408.6  852.97
   424.5   854.7   547.8  853.38   555.7  854.92   571.6  867.32   587.5  877.03
   623.3  902.78   643.2  913.59     667   922.6   702.8  941.11   750.5  971.24
#Mann= 3 , 0 , 0
       0      .1       0   389.2    .045       0   408.6      .1       0
Bank Sta=389.2,408.6
XS Rating Curve= 0 ,0
Exp/Cntr=0.3,0.1

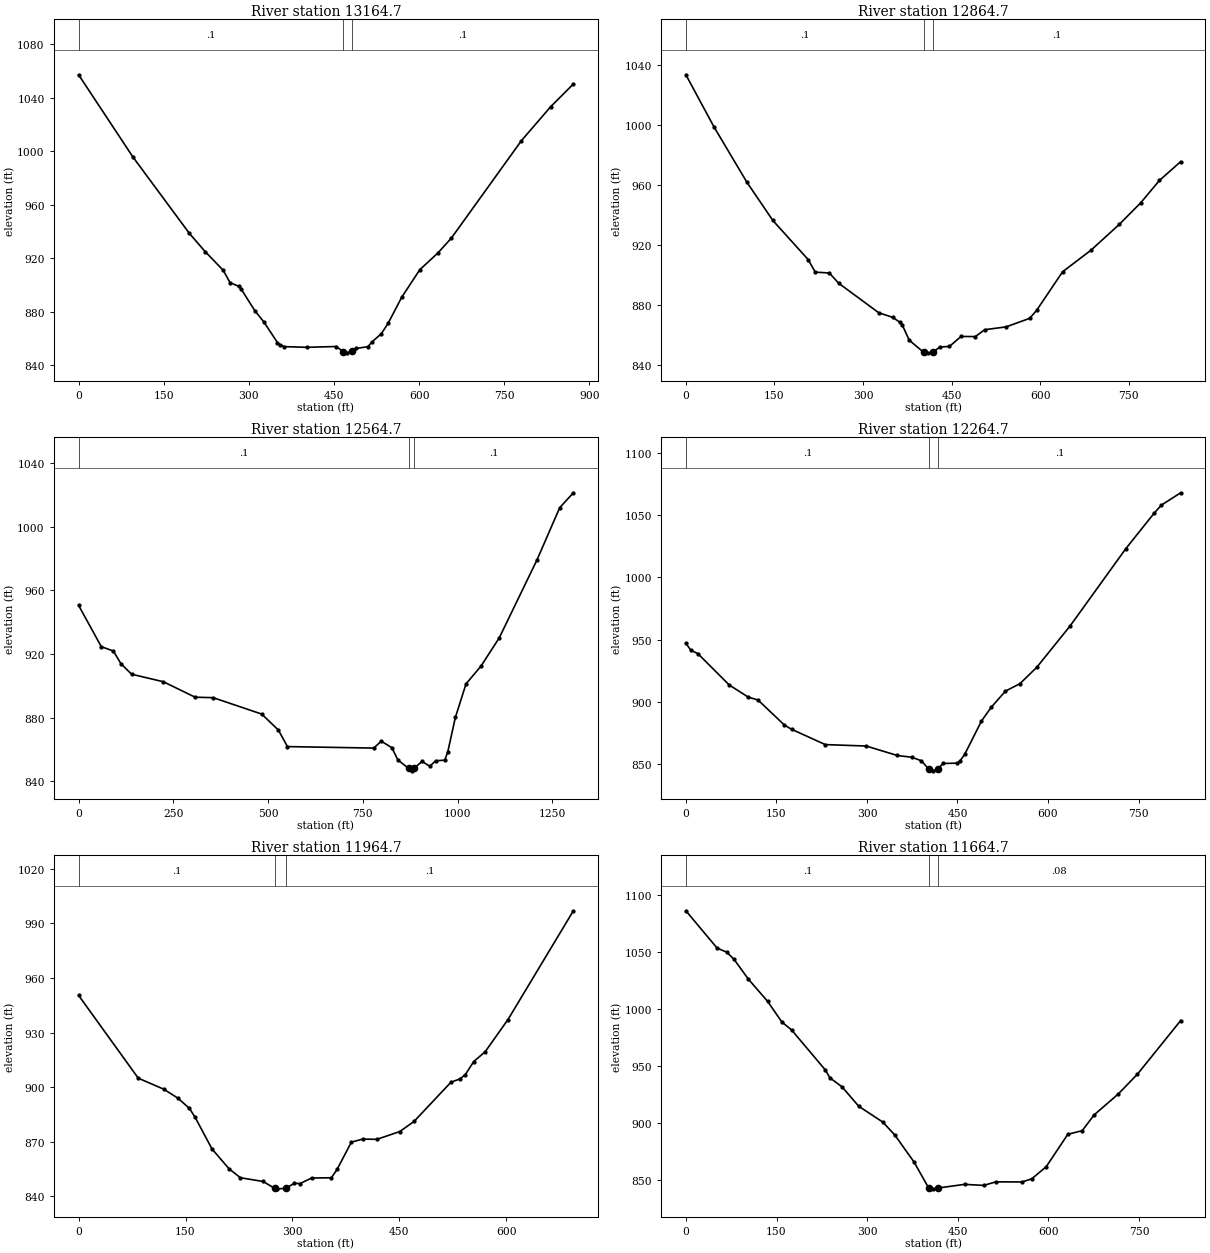
Type RM Length L Ch R = 1 ,13164.7 ,302.2,300,301
XS GIS Cut Line= 3
     1693678.152      389824.942     1694112.398      390014.202
      1694485.19      390153.582
#Sta/Elev= 30
       0 1057.28    95.5   995.9     195  938.71   222.9  925.02   254.8  911.03
   266.7  901.85   282.6  898.89   286.6  896.85   310.5   880.8   326.4  872.37
   350.3  856.96   354.3  855.27   362.2   853.9     402  853.39   453.8  853.99
   466.2  850.21   473.7  849.26   481.2  850.87   489.6  852.58   509.5  853.85
   517.5  857.64   533.4  863.61   545.3  871.32   569.2   890.8   601.1  911.44
   632.9  923.93   656.8  935.14   780.2 1008.02   831.9 1033.49   871.7  1050.4
#Mann= 3 , 0 , 0
       0      .1       0   466.2    .045       0   481.2      .1       0
Bank Sta=466.2,481.2
XS Rating Curve= 0 ,0
Exp/Cntr=0.3,0.1

Type RM Length L Ch R = 1 ,12864.7 ,314.3,300,281.7
XS GIS Cut Line= 3
     1693565.701       390067.29     1693946.444      390219.605
     1694331.532      390405.818
#Sta/Elev= 30
       0 1033.65    47.8   998.7   103.5  961.79   147.3  936.37     207   910.3
     219   901.9   242.9  901.32   258.8  894.47   326.5  874.79   350.4  871.68
   362.3  868.42   366.3   866.7   378.2  856.43   402.6  848.38   410.1  848.02
   417.6  848.26   430.1  851.93   446.1  852.26     466  858.97     490  858.86
     506  863.47     542  865.33     582  871.03     594  876.44   637.9  902.16
   685.9  916.53   733.9  933.79   769.9  948.08   801.8   963.1   837.8  975.64
#Mann= 3 , 0 , 0
       0      .1       0   402.6    .045       0   417.6      .1       0
Bank Sta=402.6,417.6
XS Rating Curve= 0 ,0
Exp/Cntr=0.3,0.1

Type RM Length L Ch R = 1 ,12564.7 ,314.4,300,284.7
XS GIS Cut Line= 3
     1693008.876      390498.453     1693887.521      390499.822
     1694314.498       390488.65
#Sta/Elev= 30
       0  950.53    59.9  924.59    91.9   921.8   111.8  913.83   139.8  907.26
   223.7  902.52   307.5   892.8   355.4   892.5   483.3  882.19   527.2  872.15
   551.2  861.75   778.8  860.82   798.8  865.14   826.7  861.07   842.7  853.34
   871.1     848   878.6  846.51   886.1  848.33   906.6  852.44   926.6  849.38
   942.5  852.83   966.5  853.25   974.4  858.56   994.4  880.14  1022.4  901.14
  1062.3  912.46  1110.2  930.13    1210  979.23  1269.8 1011.97  1305.8 1021.31
#Mann= 3 , 0 , 0
       0      .1       0   871.1    .045       0   886.1      .1       0
Bank Sta=871.1,886.1
XS Rating Curve= 0 ,0
Exp/Cntr=0.3,0.1

Type RM Length L Ch R = 1 ,12264.7 ,294.1,300,307.4
XS GIS Cut Line= 3
     1693584.623      390925.855     1693969.272      390783.416
     1694345.871      390622.176
#Sta/Elev= 30
       0  947.04       8  941.54    19.9  938.66    71.7  913.51   103.5  903.65
   119.5  901.38   163.3  881.17   175.2  877.78     231  865.48   298.7  864.33
   350.4  856.71   374.3  855.29   390.3  852.44   402.7   845.5   410.2  844.36
   417.7  846.01   426.1   850.3     450  850.54   453.9  852.14   461.9  857.58
   489.7   884.4   505.6  895.35   529.5  908.54   553.4   914.5   581.2   927.6
   636.9  961.18   728.4 1022.88   776.1 1051.93     788  1058.3   819.8 1068.18
#Mann= 3 , 0 , 0
       0      .1       0   402.7    .045       0   417.7      .1       0
Bank Sta=402.7,417.7
XS Rating Curve= 0 ,0
Exp/Cntr=0.3,0.1

Type RM Length L Ch R = 1 ,11964.7 ,319.3,300,281
XS GIS Cut Line= 3
     1693767.556      391128.662     1694044.538      391071.389
     1694447.381      390987.851
#Sta/Elev= 30
       0  950.49    83.7     905   119.5  898.94   139.4  893.98   155.4  888.43
   163.3  883.63   187.2  866.09   211.1  855.19   227.1  850.27   258.9  848.23
   275.3  844.37   278.9  844.18   290.3  844.44   302.8  847.21   310.8  847.08
   326.8  850.12   354.7  850.27   362.7  854.91   382.7  869.83   398.7  871.53
   418.6  871.39   450.6  875.66   470.6  881.21   522.5   902.8   534.5  904.48
   542.5  906.89   554.4  914.15   570.4   919.5   602.4  937.19   694.2  996.98
#Mann= 3 , 0 , 0
       0      .1       0   275.3    .045       0   290.3      .1       0
Bank Sta=275.3,290.3
XS Rating Curve= 0 ,0
Exp/Cntr=0.3,0.1

Type RM Length L Ch R = 1 ,11664.7 ,240.2,237.3,234.2
XS GIS Cut Line= 3
     1693863.981      391598.796     1694173.812      391331.041
     1694485.835      391065.814
#Sta/Elev= 30
       0 1086.46    51.7 1053.65    67.6 1050.08    79.5  1043.9   103.4 1026.42
   135.2 1006.88     159  988.62   174.9  981.77   230.6  946.69   238.5  939.62
   258.4  931.75   286.2  914.61     326  900.73   345.9  889.32   377.7   865.6
     402  842.72   409.5  842.08     417  842.78   461.2     846     493   845.1
   512.9  848.21   556.6  848.14   572.5  850.91   596.4  861.49   632.2  890.02
     656  893.21   675.9  907.15   715.6  925.38   747.4  942.83     819  989.98
#Mann= 3 , 0 , 0
       0      .1       0     402    .045       0     417     .08       0
Bank Sta=402,417
XS Rating Curve= 0 ,0
Exp/Cntr=0.3,0.1

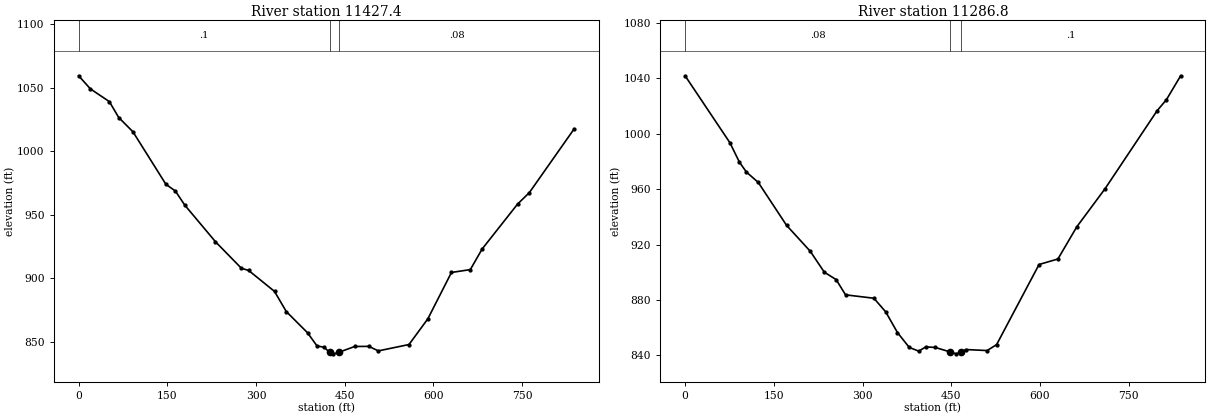
Type RM Length L Ch R = 1 ,11427.4 ,140.5,140.6,140.7
XS GIS Cut Line= 2
     1694046.606      391794.527     1694635.148      391198.173
#Sta/Elev= 30
       0 1059.49      20 1049.12    51.9 1039.15    67.8  1026.6    91.8 1015.36
   147.6  973.94   163.6  968.65   179.5  957.52   231.4  928.67   275.3  907.72
   287.3   906.1   331.2  889.53   351.1  873.66     387  856.94     403  846.59
   414.9   845.5   424.6  841.42   430.9  840.31   439.6  841.46   466.8   846.1
   490.8   846.2   506.7  842.63   558.6  847.65   590.5  867.93   630.4  904.46
   662.3   906.7   682.3  922.97   742.1   958.3   762.1  967.38   837.9 1017.66
#Mann= 3 , 0 , 0
       0      .1       0   424.6    .045       0   439.6     .08       0
Bank Sta=424.6,439.6
XS Rating Curve= 0 ,0
Exp/Cntr=0.3,0.1

Type RM Length L Ch R = 1 ,11286.8 ,220.4,222,222.7
XS GIS Cut Line= 2
     1694148.169      391880.465     1694736.711      391284.111
#Sta/Elev= 30
       0 1041.94    75.8  993.55    91.8  979.57   103.7  972.37   123.7   964.9
   171.6  933.85   211.5  915.22   235.4  900.02   255.4  894.67   271.3  883.66
   319.2  881.21   339.1  871.41   359.1  856.39     379  845.68     395  842.98
     407  846.05   422.9  845.66   447.4   842.5   458.8  841.03   466.8  842.41
   474.8  844.14   510.7   843.4   526.7  847.68   598.5  905.58   630.4  909.57
   662.3   932.8   710.2  960.39     798 1016.64   813.9 1024.69   837.9 1041.92
#Mann= 3 , 0 , 0
       0     .08       0   447.4    .045       0   466.8      .1       0
Bank Sta=447.4,466.8
XS Rating Curve= 0 ,0
Exp/Cntr=0.3,0.1