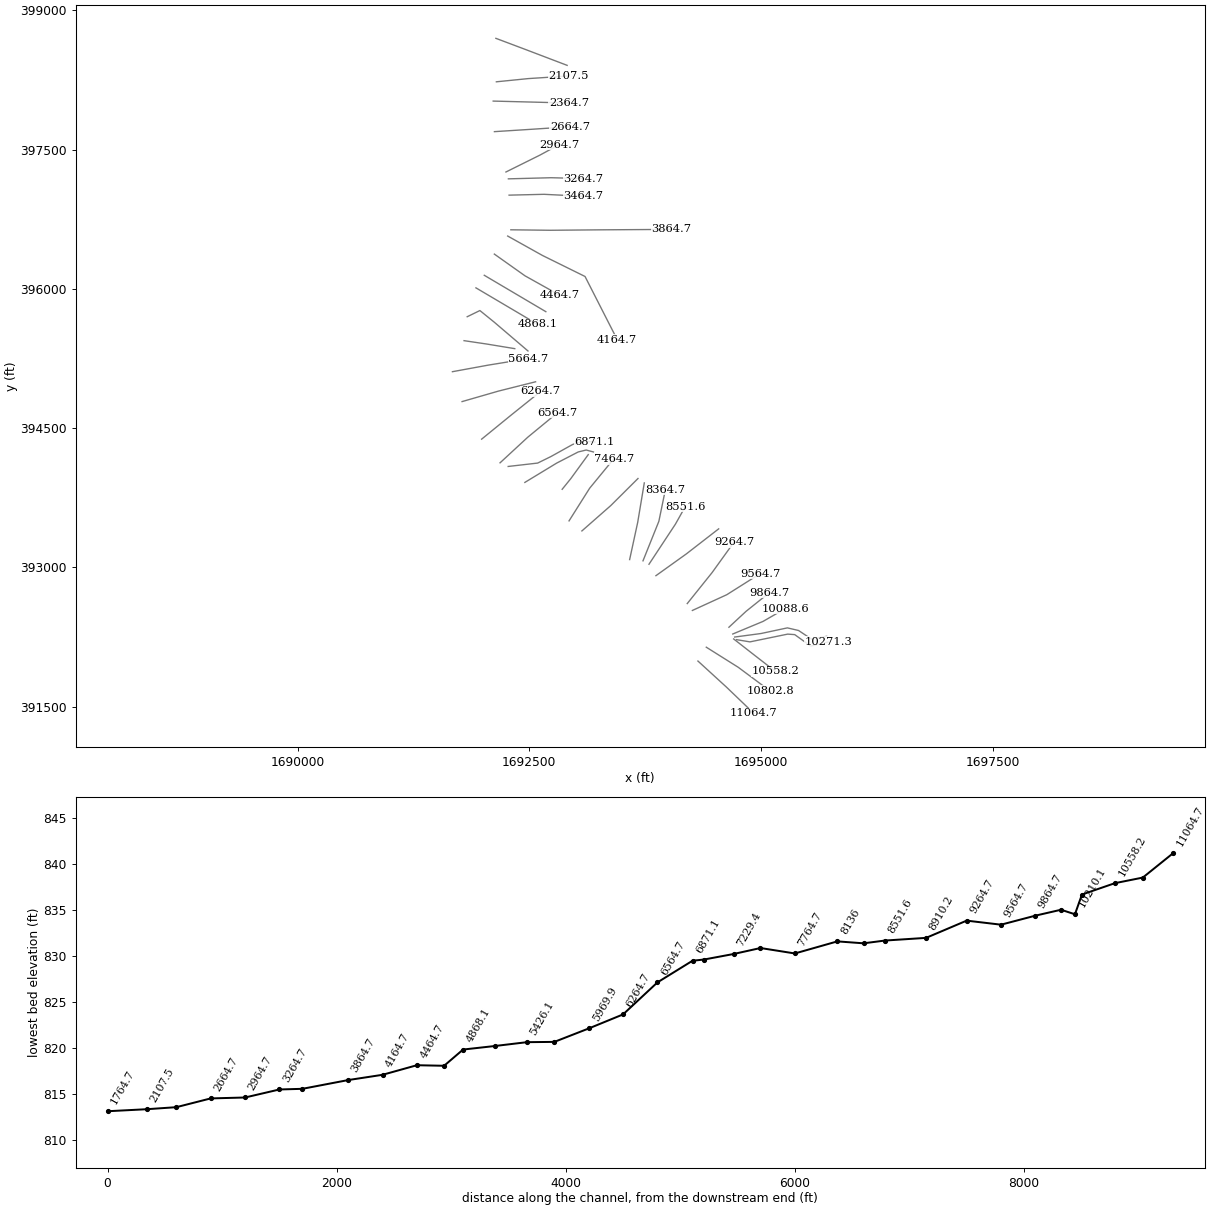
HEC-RAS study MUDRV.prj: MUDRV

--- MUDRV.g01 (geometry) --- (continued)

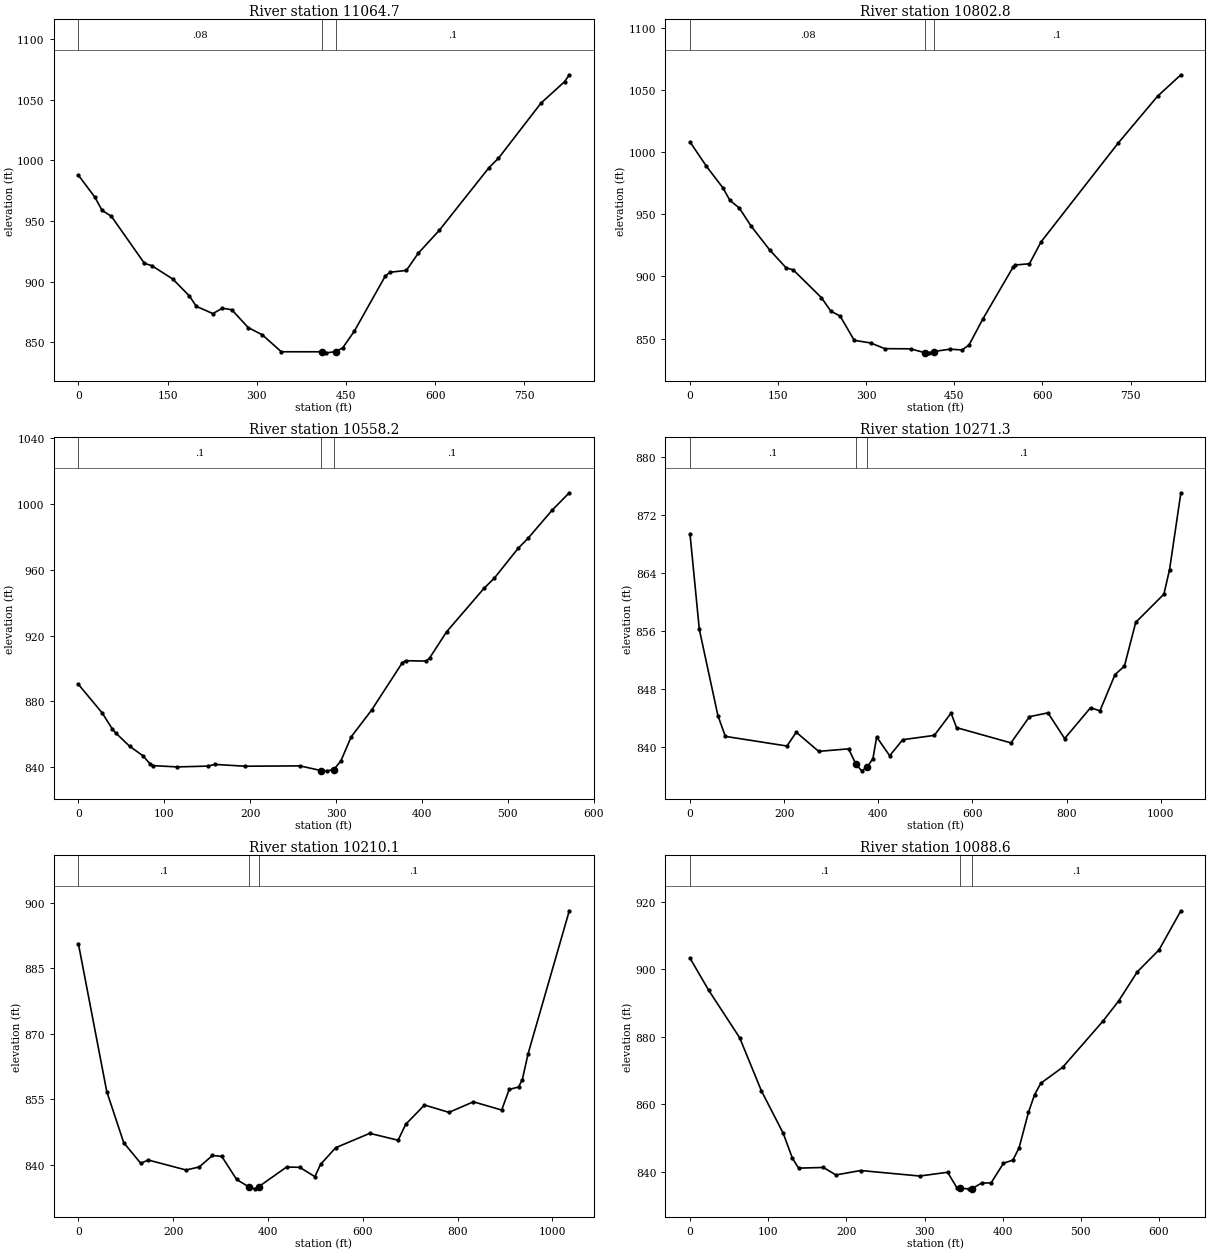
Type RM Length L Ch R = 1 ,11064.7 ,254.1,261.9,266.1
XS GIS Cut Line= 3
     1694318.754      391990.087     1694626.352      391709.235
     1694921.616      391426.374
#Sta/Elev= 30
       0  987.79    27.8  969.56    39.7  958.82    55.5  953.83   111.1  914.96
     123   913.2   158.7  902.09   186.4  888.17   198.4  879.49   226.1  873.53
     242  877.92   257.8  876.75   285.6  861.95   309.4  855.96   341.2  842.01
     409     842   416.5  841.13   432.4   842.1   444.3  845.15   464.2  859.22
   515.8  904.34   523.7  907.64   551.5   909.2   571.4  923.33   607.1  942.44
   690.4  994.04   706.3 1001.77   777.8  1047.3   817.5 1064.99   825.4  1070.7
#Mann= 3 , 0 , 0
       0     .08       0     409    .045       0   432.4      .1       0
Bank Sta=409,432.4
XS Rating Curve= 0 ,0
Exp/Cntr=0.3,0.1

Type RM Length L Ch R = 1 ,10802.8 ,240.8,244.5,238.3
XS GIS Cut Line= 3
     1694408.901      392139.191     1694753.855      391922.553
     1695097.733      391667.317
#Sta/Elev= 30
       0 1008.38      28  988.73    55.9  971.46    67.9  961.35    83.9  955.16
   103.8  940.74   135.8  921.28   163.7  906.95   175.7  905.33   223.6  883.03
   239.6  872.18   255.6  868.08   279.6  848.59   307.5  846.47   331.5  841.89
   375.4  841.73   399.8  838.62   407.3  838.51   414.8  839.56     443   841.5
   462.8   840.8   474.8  844.68   498.5  865.76   550.1  907.65     554  909.27
   577.8  910.23   597.7  927.93   728.5  1007.2   795.9 1045.15   835.6 1062.42
#Mann= 3 , 0 , 0
       0     .08       0   399.8    .045       0   414.8      .1       0
Bank Sta=399.8,414.8
XS Rating Curve= 0 ,0
Exp/Cntr=0.3,0.1

Type RM Length L Ch R = 1 ,10558.2 ,261.2,287,316
XS GIS Cut Line= 3
     1694704.167      392228.079     1694932.675      392049.877
     1695155.556      391877.602
#Sta/Elev= 30
       0  890.39    27.8  872.98    39.7  863.12    43.7  860.75    59.5   852.9
    75.4  846.92    83.4  842.12    87.3  841.05   115.1  840.28   150.8  840.78
   158.8   841.8   194.5   840.7     258  840.91   282.3  838.08   289.8   837.9
   297.3  838.62   305.6  843.94   317.6  858.53   341.4   874.8   377.1  903.52
     381  904.75   404.8  904.51   408.8   906.3   428.6  922.25   472.3  948.72
   484.2  954.82     512     973   523.9  979.29   551.6  996.15   571.5 1006.67
#Mann= 3 , 0 , 0
       0      .1       0   282.3    .045       0   297.3      .1       0
Bank Sta=282.3,297.3
XS Rating Curve= 0 ,0
Exp/Cntr=0.3,0.1

Type RM Length L Ch R = 1 ,10271.3 ,59.8,61.2,62.9
XS GIS Cut Line= 6
     1694735.634      392220.484     1694879.948      392196.612
     1695286.849      392280.163     1695362.804      392274.737
      1695535.33      392151.039     1695721.962      392195.527
#Sta/Elev= 30
       0  869.42    19.8  856.22    59.3   844.3    75.1  841.43   205.9   840.1
   225.7     842   273.4  839.36   336.9  839.71   352.8  837.55   364.8  836.67
   376.7  837.22   388.6  838.36   396.5  841.35   424.2  838.75   451.8  840.97
     519  841.57   554.5  844.64   566.2  842.64   681.8  840.53   721.1  844.15
   760.4  844.68   795.8  841.13   850.8  845.39   870.8  844.96   902.8  849.96
   922.8  851.14   946.8  857.18  1006.7  861.08  1018.7  864.48  1042.7  875.08
#Mann= 3 , 0 , 0
       0      .1       0   352.8    .045       0   376.7      .1       0
Bank Sta=352.8,376.7
XS Rating Curve= 0 ,0
Exp/Cntr=0.3,0.1

Type RM Length L Ch R = 1 ,10210.1 ,117.9,121.5,130.3
XS GIS Cut Line= 6
     1694715.017      392248.696     1694999.306      392286.673
     1695283.594      392347.437     1695404.036      392319.225
     1695542.925      392226.994     1695706.771      392256.291
#Sta/Elev= 30
       0  890.61    59.8   856.8    95.6  845.09   131.5  840.37   147.4  841.12
   227.1  838.84     255  839.54   282.8  842.17   302.4  841.95   333.7  836.68
   360.6   834.9   372.7  834.53   380.5  835.03   439.1  839.52   466.9  839.45
   498.8  837.32   510.8  840.13   542.7  843.94   614.5  847.23   674.3  845.65
   690.3  849.29     730  853.71   781.6  852.03   833.2  854.44   892.8  852.56
   908.6  857.27   928.4  857.83   936.4  859.53   948.2  865.32  1035.4  898.15
#Mann= 3 , 0 , 0
       0      .1       0   360.6    .045       0   380.5      .1       0
Bank Sta=360.6,380.5
XS Rating Curve= 0 ,0
Exp/Cntr=0.3,0.1

Type RM Length L Ch R = 1 ,10088.6 ,213.5,223.9,228.7
XS GIS Cut Line= 3
      1694694.64      392281.439      1695020.87      392417.065
     1695258.876      392554.009
#Sta/Elev= 30
       0  903.26    23.8  893.79    63.5  879.73    91.3  864.03   119.1  851.52
     131  844.08   138.9  841.15   170.7  841.34   186.6  839.13   218.3  840.44
   293.8  838.81   329.5  839.92   341.4  835.36   345.8  835.16   357.3  835.02
   360.8  835.09   373.2  836.75   385.1  836.76     401  842.58     413  843.52
     421  847.17   432.9  857.62   440.8  862.88   448.8  866.27   476.7  870.96
   528.4  884.67   548.3  890.58   572.2  899.21     600   905.7   627.9  917.26
#Mann= 3 , 0 , 0
       0      .1       0   345.8    .045       0   360.8      .1       0
Bank Sta=345.8,360.8
XS Rating Curve= 0 ,0
Exp/Cntr=0.3,0.1

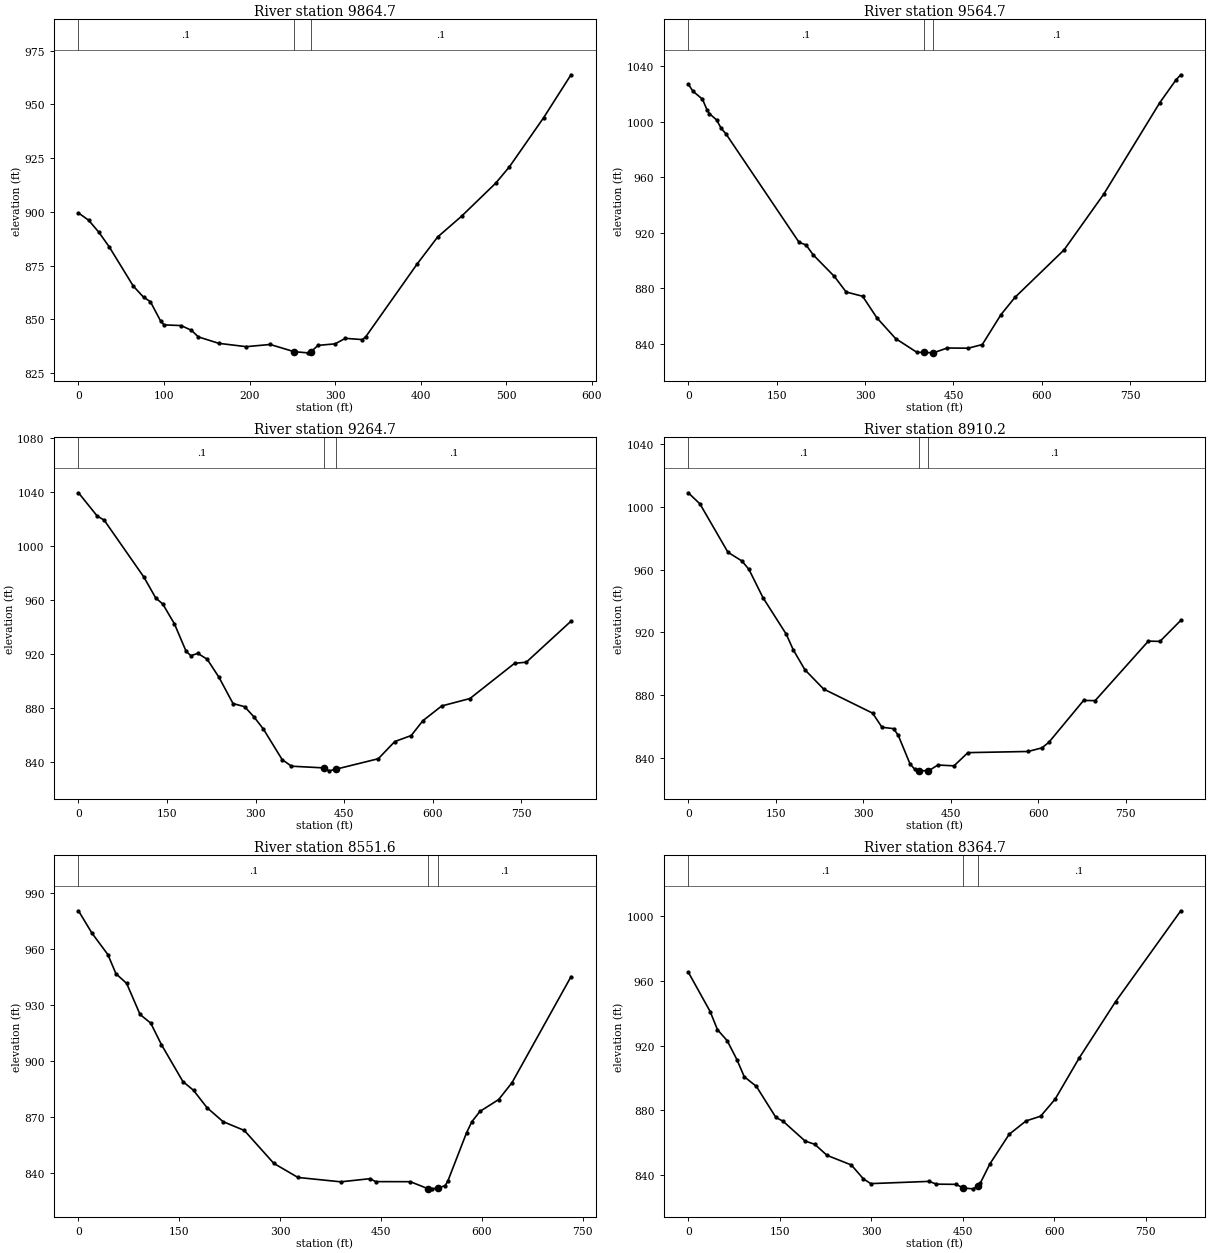
Type RM Length L Ch R = 1 ,9864.7  ,308.9,300,297.5
XS GIS Cut Line= 3
     1694652.973      392354.356     1694837.783      392525.583
     1695090.473       392727.62
#Sta/Elev= 30
       0  899.49      12  896.06      24  890.41      36  883.66      64  865.48
      76  860.29      84  858.21      96  849.19     100  847.39     120  847.07
     132  844.86     140  841.81     164   838.8     196  837.25     224  838.28
   251.9  834.92   267.9  834.38   271.9  834.98   279.9  837.85   299.9  838.56
   311.8  841.13   331.8  840.54   335.8  841.93   395.7  875.72   419.7  888.31
   447.6  897.96   487.6  913.38   503.6     921   543.5  943.81   575.5   963.8
#Mann= 3 , 0 , 0
       0      .1       0   251.9    .045       0   271.9      .1       0
Bank Sta=251.9,271.9
XS Rating Curve= 0 ,0
Exp/Cntr=0.3,0.1

Type RM Length L Ch R = 1 ,9564.7  ,281.7,300,313.6
XS GIS Cut Line= 3
     1694258.781      392535.042     1694629.686      392704.605
     1694991.686      392932.984
#Sta/Elev= 30
       0 1027.27       8  1022.1      24 1016.48      32  1008.5      36 1005.95
      48 1001.47      56   995.3      64  991.36   187.9   913.2   199.9  911.21
   211.9  904.14   247.9  888.54   267.9  877.31   295.9  874.21   319.9  858.75
   351.8  843.72   387.8  833.81   400.3  833.69   415.3  833.41   415.8   833.4
   439.5  836.88   475.2  836.75     499   839.4   530.7     861   554.5  873.47
   637.7  907.66   705.1  947.91   800.2 1013.91   827.9 1030.49   835.8 1034.02
#Mann= 3 , 0 , 0
       0      .1       0   400.3    .045       0   415.3      .1       0
Bank Sta=400.3,415.3
XS Rating Curve= 0 ,0
Exp/Cntr=0.3,0.1

Type RM Length L Ch R = 1 ,9264.7  ,364.8,354.5,343.6
XS GIS Cut Line= 3
     1694203.558      392609.314     1694471.664      392943.406
     1694709.251       393272.74
#Sta/Elev= 30
       0 1039.18    31.7 1022.03    43.6 1018.93   111.1  976.74   130.9  961.47
   142.8  957.06   162.6  942.36   182.4  922.05   190.4   918.9   202.3  920.57
   218.2   916.2     238  902.95   261.8  883.56   281.6  881.19   297.5  873.58
   313.3   864.7   345.1  842.13   360.9  837.27   416.5  835.99   424.4  833.84
   435.9  835.02     508  842.78   535.9  855.46   563.7   859.9   583.6  870.88
   615.5  881.76   663.3  887.24   738.9  913.24   758.8  914.08   834.5  944.35
#Mann= 3 , 0 , 0
       0      .1       0   416.5    .045       0   435.9      .1       0
Bank Sta=416.5,435.9
XS Rating Curve= 0 ,0
Exp/Cntr=0.3,0.1

Type RM Length L Ch R = 1 ,8910.2  ,343.5,358.6,374.1
XS GIS Cut Line= 3
     1693865.697      392909.754     1694194.335      393144.714
     1694542.409      393414.155
#Sta/Elev= 30
       0 1008.85      20 1001.78      68  971.01      92  965.46     104  960.09
     128  942.16     168  918.86     180  908.91     200  896.22     232  884.01
     316  868.66     332  859.69     352   858.8     360  854.48     380  836.45
     388  833.02   396.2  832.11   411.2  831.98   411.9  831.97   427.8  835.67
   455.5  835.15   479.3  843.55   582.4  844.29   606.2  846.58   618.1  850.13
   677.6  876.76   697.4  876.62   788.6  914.49   808.5  914.31   844.2  927.69
#Mann= 3 , 0 , 0
       0      .1       0   396.2    .045       0   411.2      .1       0
Bank Sta=396.2,411.2
XS Rating Curve= 0 ,0
Exp/Cntr=0.3,0.1

Type RM Length L Ch R = 1 ,8551.6  ,180.4,186.9,198.6
XS GIS Cut Line= 3
     1693790.747      393032.918     1694075.911      393464.841
      1694181.38      393652.341
#Sta/Elev= 30
       0  980.35    19.9  968.47    43.8  956.89    55.7  946.72    71.7   941.5
    91.6  924.91   107.5  920.28   123.4  908.78   155.3  889.07   171.2  884.34
   191.1  875.12     215  867.63   246.8  862.88   290.6  845.29   326.5  837.77
   390.2  835.43     434  837.12   441.9  835.54   493.7   835.5   520.2  831.72
   525.5  831.68   535.2  832.15   545.5  833.41   549.4  835.76   577.3  861.64
   585.3  867.62   597.2  873.06   625.1  879.43     645  888.47   732.7   945.1
#Mann= 3 , 0 , 0
       0      .1       0   520.2    .045       0   535.2      .1       0
Bank Sta=520.2,535.2
XS Rating Curve= 0 ,0
Exp/Cntr=0.3,0.1

Type RM Length L Ch R = 1 ,8364.7  ,222.1,228.8,229.8
XS GIS Cut Line= 3
     1693726.158      393069.695     1693897.302      393495.499
     1693967.839      393837.237
#Sta/Elev= 30
       0  965.55    35.9  941.14    47.9  929.88    63.8  923.12    79.8  911.35
    91.8   900.8   111.7   894.8   143.7  875.59   155.6  873.19   191.6  860.98
   207.5  858.94   227.5  852.13   267.4  846.16   287.3  837.53   299.3  834.61
   395.1     836     407  834.28     439  834.16   451.4  831.87   466.8  831.38
   474.8  832.94   478.7  834.72   494.6  846.76   526.3  865.14   554.1  873.45
   577.9  876.34   601.7   886.9   641.3  912.46   700.8  947.24   807.8 1003.52
#Mann= 3 , 0 , 0
       0      .1       0   451.4    .045       0   474.8      .1       0
Bank Sta=451.4,474.8
XS Rating Curve= 0 ,0
Exp/Cntr=0.3,0.1

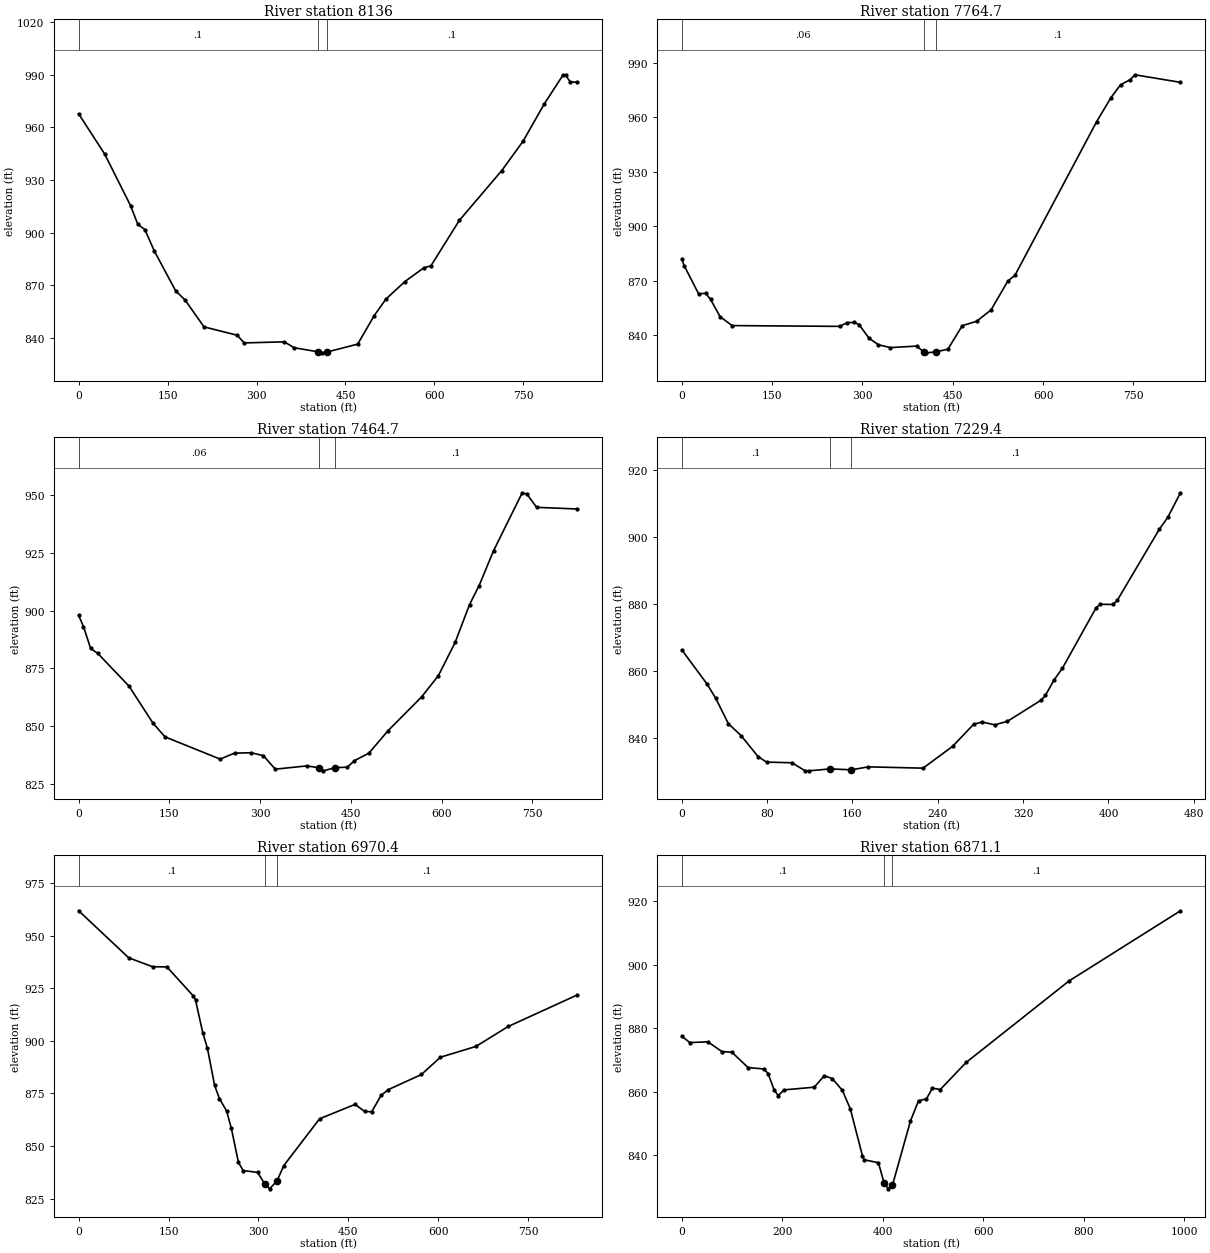
Type RM Length L Ch R = 1 ,8136    ,395,371.2,348
XS GIS Cut Line= 3
     1693582.048      393083.175      1693669.09      393484.717
      1693740.03      393909.041
#Sta/Elev= 30
       0  967.67    43.9  944.75    87.8  915.22    99.7  904.78   111.7  901.78
   127.6  889.55   163.6  866.87   179.5  861.66   211.4  846.37   267.3  841.62
   279.2  837.24     347  837.86     363  834.53   403.4  832.19   410.9  831.59
   418.4  832.02   470.6  836.56   498.5   852.8   518.4  862.28   550.3  872.19
   582.2  880.02   594.1  881.13   641.9  906.95   713.6  935.39   749.5   952.1
   785.3  973.36   817.2  989.91   821.2   989.7   829.1  985.83   841.1  985.64
#Mann= 3 , 0 , 0
       0      .1       0   403.4    .045       0   418.4      .1       0
Bank Sta=403.4,418.4
XS Rating Curve= 0 ,0
Exp/Cntr=0.3,0.1

Type RM Length L Ch R = 1 ,7764.7  ,289.2,300,303.7
XS GIS Cut Line= 3
     1693067.131      393391.794     1693378.335      393664.751
     1693672.085      393956.548
#Sta/Elev= 30
       0  882.04       4  878.26    27.9  862.81    39.8     863    47.8  859.68
    63.7  850.17    83.6  845.28   262.7  844.84   274.6  846.94   286.6     847
   294.5  845.78   310.5  838.48   326.4  834.75   346.3  833.16   390.1     834
     402   830.7     406  830.28   421.4  830.79   441.8  832.27   465.7  845.21
   489.6  847.64   513.5  853.91   541.4  869.79   553.3  873.02   688.6  957.38
   712.5  970.67   728.5  977.81   744.4  980.55   752.4  983.29     828  979.13
#Mann= 3 , 0 , 0
       0     .06       0     402    .045       0   421.4      .1       0
Bank Sta=402,421.4
XS Rating Curve= 0 ,0
Exp/Cntr=0.3,0.1

Type RM Length L Ch R = 1 ,7464.7  ,238.9,235.4,237.1
XS GIS Cut Line= 3
     1692928.424      393499.993     1693150.867      393852.073
     1693410.232      394167.278
#Sta/Elev= 30
       0  897.89     7.9   893.1    19.8  883.64    31.7  881.48    83.3  867.38
     123   851.4   142.8  845.52     234  835.92   257.8  838.52   285.6  838.66
   305.4  837.41   325.2  831.59   376.8  832.99   396.6  832.26   404.6  830.87
     424  832.25   444.2  832.44   456.1  835.26   479.9  838.48   511.6  848.18
   567.1  862.75   594.8  871.91   622.5  886.21   646.3  902.52   662.2  910.74
     686  925.74   733.5  950.76   741.4  950.14   757.3  944.48   824.7  943.77
#Mann= 3 , 0 , 0
       0     .06       0   396.6    .045       0     424      .1       0
Bank Sta=396.6,424
XS Rating Curve= 0 ,0
Exp/Cntr=0.3,0.1

Type RM Length L Ch R = 1 ,7229.4  ,272.7,258.9,244
XS GIS Cut Line= 3
     1692854.362      393840.467     1692946.973      393954.811
     1693135.612      394213.731
#Sta/Elev= 30
       0  866.34    23.9  856.04    31.8  851.88    43.8  844.25    55.7  840.71
    71.6  834.44    79.5  832.83   103.4  832.63   115.3  830.29   119.3  830.22
   139.2  830.81     159  830.52   174.8  831.41   226.2  831.02   253.9  837.53
   273.7  844.14   281.6  844.78   293.5  843.95   305.3     845     337  851.34
   340.9  852.73   348.8  857.25   356.8  860.82   388.4  878.88   392.4  879.92
   404.2  879.87   408.2  881.08   447.7  902.32   455.6  905.86   467.5   913.2
#Mann= 3 , 0 , 0
       0      .1       0   139.2    .045       0     159      .1       0
Bank Sta=139.2,159
XS Rating Curve= 0 ,0
Exp/Cntr=0.3,0.1

Type RM Length L Ch R = 1 ,6970.4  ,102.5,99.3,96
XS GIS Cut Line= 5
     1692451.758      393914.425     1692795.508      394122.759
     1693027.279       394242.55     1693113.216      394263.384
     1693191.341       394242.55
#Sta/Elev= 30
       0  961.89    83.6   939.5   123.4  935.28   147.2  935.19     191  921.46
     195   919.4     207  903.94   214.9  896.41   226.8  878.84   234.8  872.56
   246.7  866.73   254.7  858.48   266.6  842.15   274.6  838.31   298.5  837.43
   310.4  832.04   318.4  829.62   330.8   833.3   342.3  840.71     402  862.95
   461.2   869.8   477.1  866.43   488.9  866.28   504.7  874.11   516.6  876.81
   571.9  884.01   603.6  892.23   662.8  897.36   716.7  906.85   832.1  921.88
#Mann= 3 , 0 , 0
       0      .1       0   310.4    .045       0   330.8      .1       0
Bank Sta=310.4,330.8
XS Rating Curve= 0 ,0
Exp/Cntr=0.3,0.1

Type RM Length L Ch R = 1 ,6871.1  ,295.2,306.4,314.8
XS GIS Cut Line= 6
      1692272.07        394086.3     1692589.779      394122.759
     1692733.008      394193.071     1692967.383       394323.28
      1693084.57      394359.738     1693206.966      394349.321
#Sta/Elev= 30
       0  877.57      16  875.56      52  875.78      80  872.72    99.9  872.51
   131.9   867.7   163.9  867.23   171.9  865.79   183.9  860.68   191.9  858.86
   203.9  860.66   263.8   861.5   283.8  865.12   299.8  864.21   319.8   860.5
   335.8  854.58   359.7  839.94   363.7  838.63   391.6  837.71   403.1  831.19
   411.5  829.49   419.5  830.63   455.4  850.86   471.4  857.23   487.2  857.83
   499.1   861.2   514.8  860.77   566.1  869.28   771.2  894.97     993  917.06
#Mann= 3 , 0 , 0
       0      .1       0   403.1    .045       0   419.5      .1       0
Bank Sta=403.1,419.5
XS Rating Curve= 0 ,0
Exp/Cntr=0.3,0.1

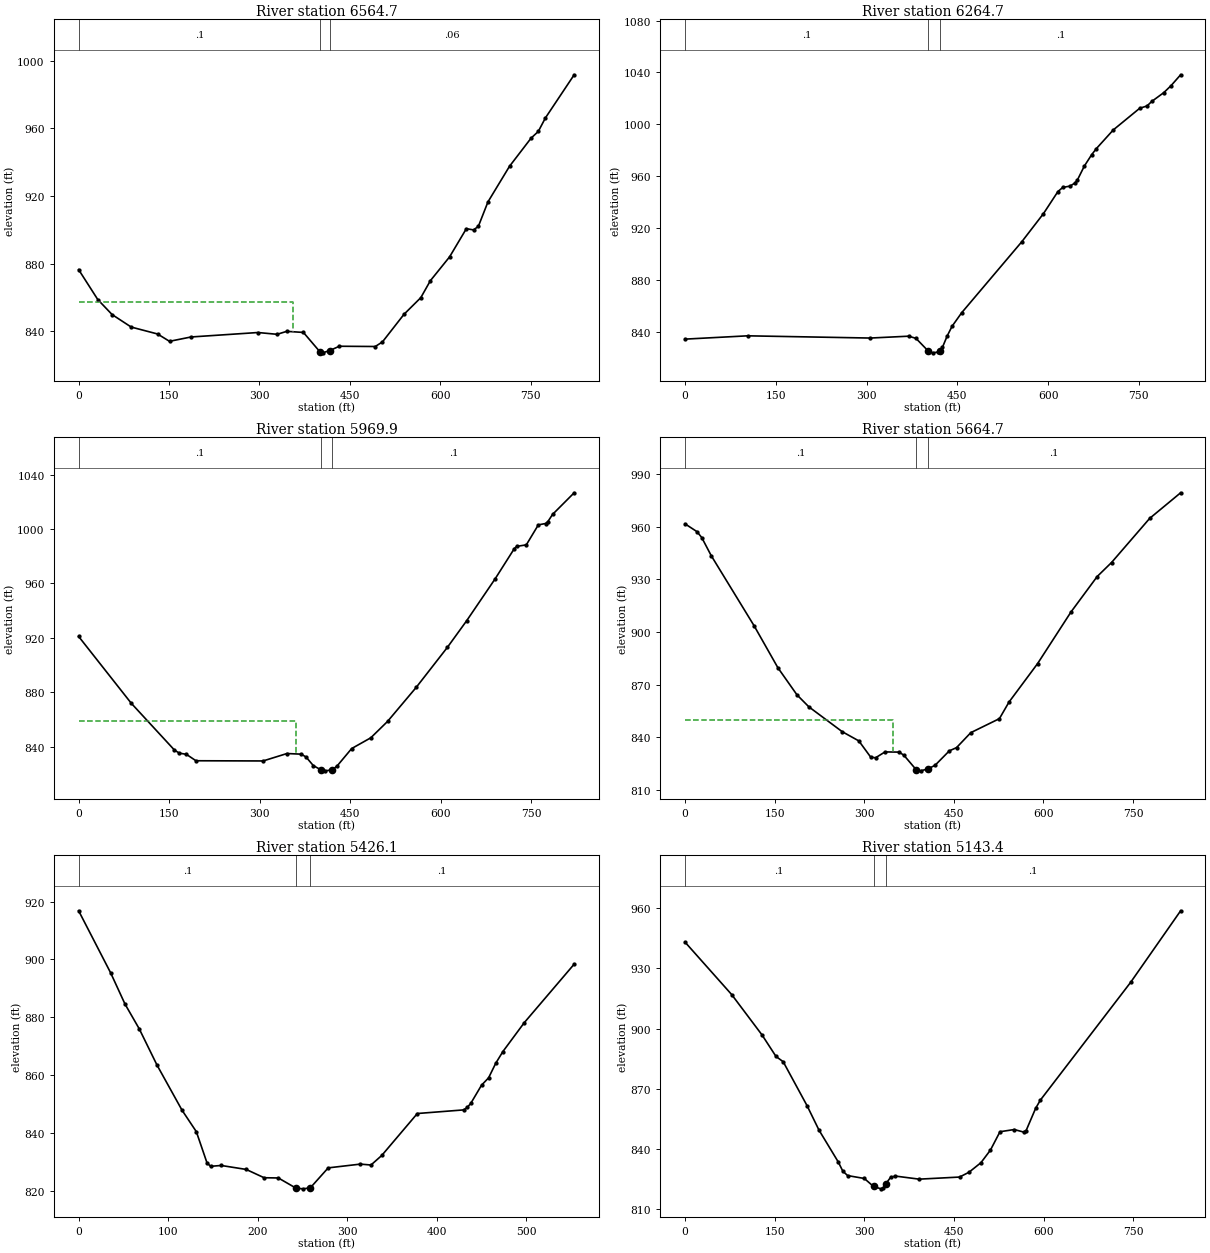
Type RM Length L Ch R = 1 ,6564.7  ,302.3,300,299.6
XS GIS Cut Line= 3
     1692184.148      394125.327     1692484.573      394402.525
      1692804.17       394664.98
#Sta/Elev= 30
       0   876.4    31.8  858.67    55.6  849.78    87.3  842.39     131   838.3
   150.8  833.96   186.5  836.53   297.6  839.17   329.4  838.11   345.3  839.86
     373  839.22   401.3  827.38   404.8  827.14   416.3  828.44   432.6  831.04
   492.3  830.89   504.2  833.63     540  849.99   567.8  859.81   583.7  869.86
   615.6  883.98   643.4  900.65   655.3  899.92   663.3  902.02   679.2  916.48
     715  937.58   750.8  954.25   762.7  958.18   774.6  966.23   822.3  991.76
#Mann= 3 , 0 , 0
       0      .1       0   401.3    .045       0   416.3     .06       0
#XS Ineff= 2 , 0
          355.57  857.29
Permanent Ineff=
       F       F
Bank Sta=401.3,416.3
XS Rating Curve= 0 ,0
Exp/Cntr=0.3,0.1

Type RM Length L Ch R = 1 ,6264.7  ,309.9,294.8,278.5
XS GIS Cut Line= 3
     1691985.499      394380.393     1692302.878      394638.968
     1692622.609      394895.065
#Sta/Elev= 30
       0  834.25   103.3   836.8     306  835.08   369.6  836.52   381.6  834.83
   401.9  825.04   409.4  823.67   417.3  824.25   421.3  825.37   425.3  827.88
   433.2  836.72   441.2  844.14   457.1   854.6   556.5   909.4   592.3  931.09
   616.2  948.12   624.2  951.29   636.1  952.31     644   954.6     648  956.68
   659.9  967.81   671.9  976.52   679.8  981.28   707.7  995.66   751.4 1012.38
   763.4 1014.13   771.3 1017.65   791.2 1024.45   803.1 1029.79     819  1038.2
#Mann= 3 , 0 , 0
       0      .1       0   401.9    .045       0   421.3      .1       0
Bank Sta=401.9,421.3
XS Rating Curve= 0 ,0
Exp/Cntr=0.3,0.1

Type RM Length L Ch R = 1 ,5969.9  ,308.9,305.2,301.7
XS GIS Cut Line= 3
     1691774.729      394785.155     1692167.484      394898.315
     1692567.547      394998.456
#Sta/Elev= 30
       0  921.01    87.3  871.83   158.7  837.48   166.7  835.21   178.6   834.3
   194.4  829.59   305.6  829.44   345.2   834.9     369  834.44     377  832.26
   388.9  826.01   401.2  822.98   408.7  822.17   420.6  822.94   428.6  825.92
   452.4  838.56   484.1  846.47   511.8  858.48   559.4  883.58     611  912.99
   642.7  932.42   690.3  963.51     722  985.69     726  987.29   741.8  988.39
   761.7 1003.09   773.6 1004.09   777.5  1005.5   785.4 1010.83   821.1  1026.7
#Mann= 3 , 0 , 0
       0      .1       0   401.2    .045       0   420.6      .1       0
#XS Ineff= 2 , 0
          360.66  858.63
Permanent Ineff=
       F       F
Bank Sta=401.2,420.6
XS Rating Curve= 0 ,0
Exp/Cntr=0.3,0.1

Type RM Length L Ch R = 1 ,5664.7  ,251.2,238.7,226.4
XS GIS Cut Line= 3
     1691670.508      395107.134     1692058.529       395178.24
     1692488.112      395247.765
#Sta/Elev= 30
       0  961.75    19.9  957.31    27.9  953.92    43.8  943.56   115.6  903.51
   155.4  879.55   187.3  864.09   207.2  857.25     263  843.07   290.9  837.78
   310.8  828.48   318.8  828.14   334.7   831.5   358.6  831.39   366.6  829.48
     387  821.29   394.5  820.69   406.5  821.82   418.4  823.83   442.4  832.12
   454.4  833.94   478.3   842.5   526.2   850.5   542.2  859.94   590.1  881.94
     646  911.42   689.9  931.69   713.9  939.68   777.8  964.91   829.6  979.52
#Mann= 3 , 0 , 0
       0      .1       0     387    .045       0   406.5      .1       0
#XS Ineff= 2 , 0
          348.78   849.9
Permanent Ineff=
       F       F
Bank Sta=387,406.5
XS Rating Curve= 0 ,0
Exp/Cntr=0.3,0.1

Type RM Length L Ch R = 1 ,5426.1  ,302.9,282.7,262.9
XS GIS Cut Line= 3
     1691795.964      395441.404     1692040.264      395405.096
     1692342.839      395355.466
#Sta/Elev= 30
       0  916.82    35.8  895.33    51.8  884.56    67.7     876    87.6  863.43
   115.5  847.86   131.5  840.43   143.4  829.65   147.4  828.45   159.3  828.74
   187.2  827.37   207.2   824.5   223.1  824.42     243  820.87     251  820.66
   258.9  821.03   278.8  827.91   314.7  829.21   326.6   828.9   338.6  832.19
   378.4  846.71   430.2  847.96   434.1  848.81   438.1  850.22   450.1   856.5
     458  859.05     466   864.1     474  868.15   497.8  878.11   553.6  898.36
#Mann= 3 , 0 , 0
       0      .1       0     243    .045       0   258.9      .1       0
Bank Sta=243,258.9
XS Rating Curve= 0 ,0
Exp/Cntr=0.3,0.1

Type RM Length L Ch R = 1 ,5143.4  ,269.5,275.3,281.2
XS GIS Cut Line= 4
     1691829.818      395699.216     1691966.702      395765.827
     1692121.985      395640.198     1692485.395      395330.432
#Sta/Elev= 30
       0  942.94    78.1  916.84   128.8  896.79   152.2  886.09   164.2  883.48
   204.2  861.58   224.1  849.47   256.1  833.75   264.1     829   272.1  826.83
     300   825.4   315.4  821.41     328  820.24     332  820.73     336  822.75
     344  825.97     352  826.59   391.8  825.06   459.4   826.1   475.3  828.51
   495.2  833.24   511.1  839.51   527.1  848.65   550.9  849.74   566.8  848.48
   570.8  849.19   586.8  860.31   594.7  864.38   745.9  923.01   829.5  958.57
#Mann= 3 , 0 , 0
       0      .1       0   315.4    .045       0     336      .1       0
Bank Sta=315.4,336
XS Rating Curve= 0 ,0
Exp/Cntr=0.3,0.1

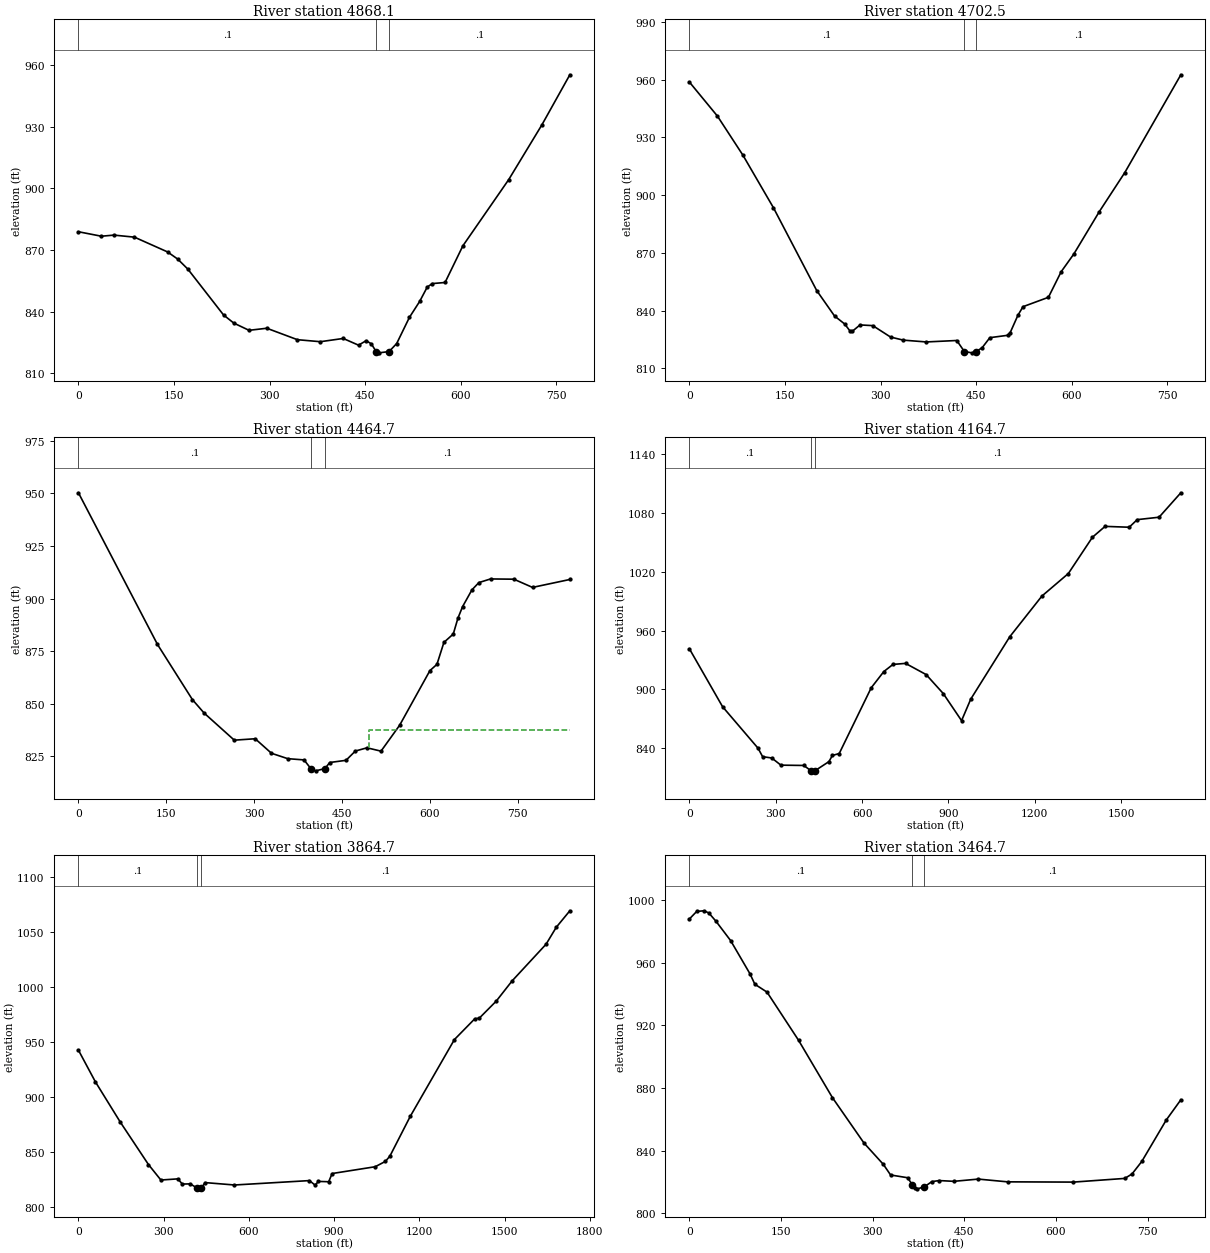
Type RM Length L Ch R = 1 ,4868.1  ,165.3,165.6,165.1
XS GIS Cut Line= 2
     1691924.211      396010.239     1692588.273      395618.312
#Sta/Elev= 30
       0   878.9      36  876.72    55.9  877.26    87.9  876.26   139.8  869.07
   155.8  865.57   171.8  860.65   227.7  838.33   243.7  834.38   267.7  830.84
   295.6  831.85   343.6  826.27   379.6  825.29   415.5  826.87   439.5   823.6
   451.5  825.78   459.5  824.28   467.4  820.38   471.4  819.86   487.4  820.47
   499.4   824.4   519.4  837.17   535.4   844.9   547.4  851.97   555.4  853.63
   575.3  854.16   603.3  872.06   675.2  904.33   727.2  930.99   771.1  955.43
#Mann= 3 , 0 , 0
       0      .1       0   467.4    .045       0   487.4      .1       0
Bank Sta=467.4,487.4
XS Rating Curve= 0 ,0
Exp/Cntr=0.3,0.1

Type RM Length L Ch R = 1 ,4702.5  ,244.2,237.8,229.4
XS GIS Cut Line= 2
     1692014.054      396145.656     1692678.117      395753.729
#Sta/Elev= 30
       0  958.76      44  941.06    83.9   920.8   131.8   893.5   199.8  850.42
   227.7  837.24   243.7  833.06   251.7  829.55   255.7  829.32   267.7   832.6
   287.7  832.24   315.6   826.3   335.6   824.7   371.6  823.76   419.5  824.51
   431.5  818.75   443.5   818.1   450.1  818.75   459.5  820.84   471.4  825.98
   499.4  827.21   503.4  828.65   515.4  837.58   523.4  842.07   563.3  846.95
   583.3  860.23   603.3   869.5   643.2  891.48   683.2  911.77   771.1  962.55
#Mann= 3 , 0 , 0
       0      .1       0   431.5    .045       0   450.1      .1       0
Bank Sta=431.5,450.1
XS Rating Curve= 0 ,0
Exp/Cntr=0.3,0.1

Type RM Length L Ch R = 1 ,4464.7  ,296.1,300,304.9
XS GIS Cut Line= 3
     1692122.687      396374.047     1692453.269      396139.893
      1692832.11      395928.444
#Sta/Elev= 30
       0  950.22     135  878.18   194.6  851.99   214.5  845.63   266.1  832.73
   301.8   833.4   329.6   826.5   357.4  823.94   385.2  823.35   397.6  818.94
   405.1  818.16     421  819.24     429  822.12   456.8  823.15   472.8  827.56
   492.7   829.1   516.6  827.51   548.4  839.81   600.1  865.76   612.1  868.74
     624  879.17     640  883.15   647.9  890.65   655.9  896.17   671.8   904.1
   683.7  907.57   703.6   909.3   743.4  909.18   775.3  905.28     839  909.04
#Mann= 3 , 0 , 0
       0      .1       0   397.6    .045       0     421      .1       0
#XS Ineff= 2 , 0
                          496.89          837.52
Permanent Ineff=
       F       F
Bank Sta=397.6,421
XS Rating Curve= 0 ,0
Exp/Cntr=0.3,0.1

Type RM Length L Ch R = 1 ,4164.7  ,281.4,300,317
XS GIS Cut Line= 4
     1692266.578       396568.47     1692641.271      396359.429
     1693100.821      396132.893     1693449.056      395450.811
#Sta/Elev= 30
       0  941.37   115.2  882.41   238.4  840.16   254.3  831.52     286  830.21
   317.8  822.91   397.3   822.6   421.6  817.38     433  817.12   436.6   817.3
   484.7  826.52   496.6  832.77   520.4  834.76   631.6  901.73   675.3  918.22
   707.1   925.5   750.8  926.55   822.3  915.16   881.8  895.84   945.4  868.24
   977.3  890.14  1112.9  953.69  1224.6  995.14  1316.4 1018.07  1400.1 1055.03
    1444 1066.08  1527.8 1065.21  1555.7 1072.95  1631.5 1075.41  1707.2  1100.3
#Mann= 3 , 0 , 0
       0      .1       0   421.6    .045       0   436.6      .1       0
Bank Sta=421.6,436.6
XS Rating Curve= 0 ,0
Exp/Cntr=0.3,0.1

Type RM Length L Ch R = 1 ,3864.7  ,397.9,400.1,397.9
XS GIS Cut Line= 4
     1692300.716       396635.78     1692726.165      396630.569
     1693277.656      396635.485     1694030.653      396640.048
#Sta/Elev= 30
       0  942.77    59.6     914   147.1   877.4   246.5  838.68   290.3  824.57
   349.9  825.62   365.8   820.9   393.7  821.07     418  817.23   425.5  816.55
     433  817.07   445.5  822.24   549.4  820.05   813.1  824.05   833.1  819.97
   845.1   823.3   881.1  823.02   893.1  830.48  1044.7  836.66  1080.6  841.51
  1096.5  846.32  1168.2  882.52  1323.6  952.39  1395.3   971.3  1411.3   971.9
    1471  987.42  1526.8  1005.8  1646.3 1039.17  1682.2 1054.58    1730  1069.6
#Mann= 3 , 0 , 0
       0      .1       0     418    .045       0     433      .1       0
Bank Sta=418,433
XS Rating Curve= 0 ,0
Exp/Cntr=0.3,0.1

Type RM Length L Ch R = 1 ,3464.7  ,196.2,199.9,201.7
XS GIS Cut Line= 3
     1692281.619      397009.043     1692658.456      397018.019
     1693085.438      396996.891
#Sta/Elev= 30
       0  988.09    11.9  992.89    23.8  993.31    31.7  991.94    43.6  986.55
    67.4  974.28    99.2  952.98   107.1  946.35     127  941.33   178.6  910.57
   234.1  873.88   285.7  844.89   317.4  831.25   329.3  824.46   357.1   822.7
     365  818.17     369  816.03     373   815.6   384.4  816.85   396.9  820.23
   408.9  820.89   432.9   820.4   472.8  821.83   520.8  820.07   628.6  819.91
   712.6  822.26   724.5  825.11   740.5  833.12   780.5  859.58   804.4  872.51
#Mann= 3 , 0 , 0
       0      .1       0     365    .045       0   384.4      .1       0
Bank Sta=365,384.4
XS Rating Curve= 0 ,0
Exp/Cntr=0.3,0.1

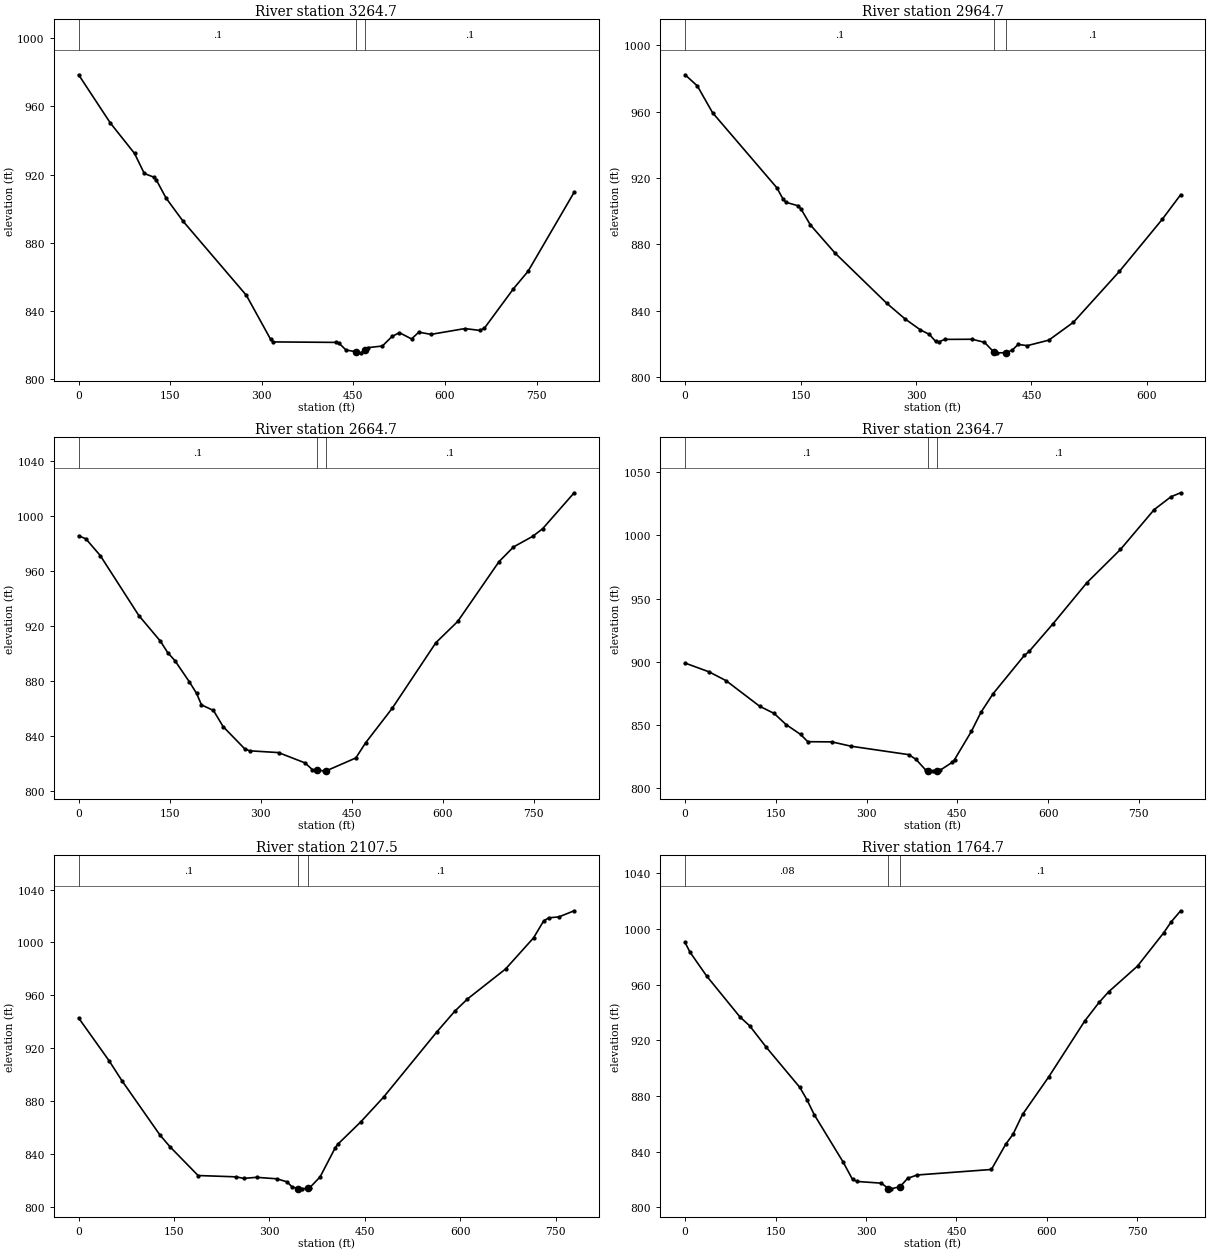
Type RM Length L Ch R = 1 ,3264.7  ,285.9,300,319.3
XS GIS Cut Line= 3
     1692274.063      397184.659     1692735.662      397196.735
     1693085.438      397187.863
#Sta/Elev= 30
       0  978.54    51.8  950.33    91.6  932.41   107.5   920.7   123.4  918.48
   127.4  916.79   143.3  906.21   171.2  892.62   274.7  849.26   314.5  823.42
   318.4  821.94     422  821.65   425.9  821.37   437.9  817.18   454.3  816.18
   461.8  815.53   469.3  816.97   473.7  818.58   497.5  819.53   513.4  825.16
   525.4  827.34   545.2  823.69   557.2  827.65   577.1  826.36   632.7  829.76
   656.6  828.69   664.5  829.95   712.2  853.12   736.1  863.35   811.6  909.69
#Mann= 3 , 0 , 0
       0      .1       0   454.3    .045       0   469.3      .1       0
Bank Sta=454.3,469.3
XS Rating Curve= 0 ,0
Exp/Cntr=0.3,0.1

Type RM Length L Ch R = 1 ,2964.7  ,314.4,300,284.4
XS GIS Cut Line= 3
     1692247.813      397258.459     1692613.995      397440.127
     1692820.703      397552.081
#Sta/Elev= 30
       0   982.3    15.9  975.59    35.7  959.42   119.1  914.24     127  907.59
     131  905.43   146.8  903.32   150.8   901.2   162.7  891.83   194.5  874.96
   261.9  844.58   285.7  835.13   305.6  828.54   317.5  825.73   325.4  821.57
   329.4  821.21   337.3  822.77     373  822.85   388.9  821.01   401.3  815.04
   404.8  814.66   416.3  814.75   424.7  816.17   432.7  819.72   444.6     819
   472.5  822.31   504.4  833.05   564.2  863.74   619.9  895.16   643.8  909.98
#Mann= 3 , 0 , 0
       0      .1       0   401.3    .045       0   416.3      .1       0
Bank Sta=401.3,416.3
XS Rating Curve= 0 ,0
Exp/Cntr=0.3,0.1

Type RM Length L Ch R = 1 ,2664.7  ,303.9,300,295.6
XS GIS Cut Line= 3
     1692123.633      397693.071     1692523.655      397718.486
     1692938.513      397745.891
#Sta/Elev= 30
       0  985.49    11.9  983.28    35.7  971.07    99.2  927.49   134.9  908.78
   146.8   900.5   158.7  894.68   182.6  879.18   194.5   870.8   202.4  862.52
   222.2  858.46   238.1  846.72   273.8  830.52   281.8  829.13   329.4  827.83
     373  820.34     385  815.52   393.3  815.01   404.8  814.56   408.3   814.6
   456.8  823.93   472.8  834.88   516.8  860.07   588.7  907.74   624.7   923.2
   692.7  966.66   716.6  977.35   748.6  985.16   764.6  990.61   816.6 1016.75
#Mann= 3 , 0 , 0
       0      .1       0   393.3    .045       0   408.3      .1       0
Bank Sta=393.3,408.3
XS Rating Curve= 0 ,0
Exp/Cntr=0.3,0.1

Type RM Length L Ch R = 1 ,2364.7  ,254,257.2,259.4
XS GIS Cut Line= 3
      1692110.21      398022.287     1692519.578      398011.882
     1692928.939      398001.215
#Sta/Elev= 30
       0  898.93    39.8  891.95    67.6  885.04   123.2  864.77   147.1  859.06
     167   850.2   190.8  842.46   202.8  836.68   242.5  836.54   274.3   833.1
   369.7  826.43   381.7  822.66   397.6  814.26     402  813.69   409.5  813.61
     417  813.79   421.4  814.08   441.3  820.26   445.3  822.49   473.1  844.78
     489  859.97   508.9  874.59   560.6  904.94   568.5   908.1   608.3  930.18
     664  962.54   719.6  988.92   775.3 1020.45   803.1 1030.63     819 1033.76
#Mann= 3 , 0 , 0
       0      .1       0     402    .045       0     417      .1       0
Bank Sta=402,417
XS Rating Curve= 0 ,0
Exp/Cntr=0.3,0.1

Type RM Length L Ch R = 1 ,2107.5  ,357.8,342.8,327.4
XS GIS Cut Line= 3
     1692144.488      398230.032     1692490.344      398264.722
     1692920.964      398292.668
#Sta/Elev= 30
       0  942.78    47.9  910.39    67.9  895.42   127.8  854.18   143.8  845.18
   187.8  823.48   247.7  822.47   259.7   821.3   279.7  822.11   311.6  820.99
   327.6   818.7   335.6  814.84   345.6  813.52   351.6  813.39   360.6  813.93
   363.6  814.38   379.6   822.4   403.5  844.57   407.5  847.18   443.5  864.06
   479.4  882.82   563.4  932.36   591.3  947.87   611.3  957.16   671.2  979.87
   715.2 1003.44   731.2 1016.32   739.2 1018.62   755.1 1019.35   779.1 1023.97
#Mann= 3 , 0 , 0
       0      .1       0   345.6    .045       0   360.6      .1       0
Bank Sta=345.6,360.6
XS Rating Curve= 0 ,0
Exp/Cntr=0.3,0.1

Type RM Length L Ch R = 1 ,1764.7  ,307.2,300,295.8
XS GIS Cut Line= 3
     1692139.258       398698.28     1692466.006      398575.357
     1692907.789      398407.291
#Sta/Elev= 30
       0  990.37     7.9  983.56    35.7  966.28    91.2  936.71   107.1  930.44
   134.9  914.87   190.4  886.07   202.3  877.08   214.2  866.48   261.8  832.65
   277.7   819.9   285.6  818.47   325.3  817.25   337.2  813.41   341.2  813.17
   356.6  814.73     369  820.71   384.8  823.13     508   827.1   531.8  845.34
   543.7  852.34   559.6  866.68   603.3  893.86   662.9  933.99   686.7  947.35
   702.6  954.98   750.3  973.41     794  997.51   805.9 1005.08   821.8 1013.18
#Mann= 3 , 0 , 0
       0     .08       0   337.2    .045       0   356.6      .1       0
Bank Sta=337.2,356.6
XS Rating Curve= 0 ,0
Exp/Cntr=0.3,0.1