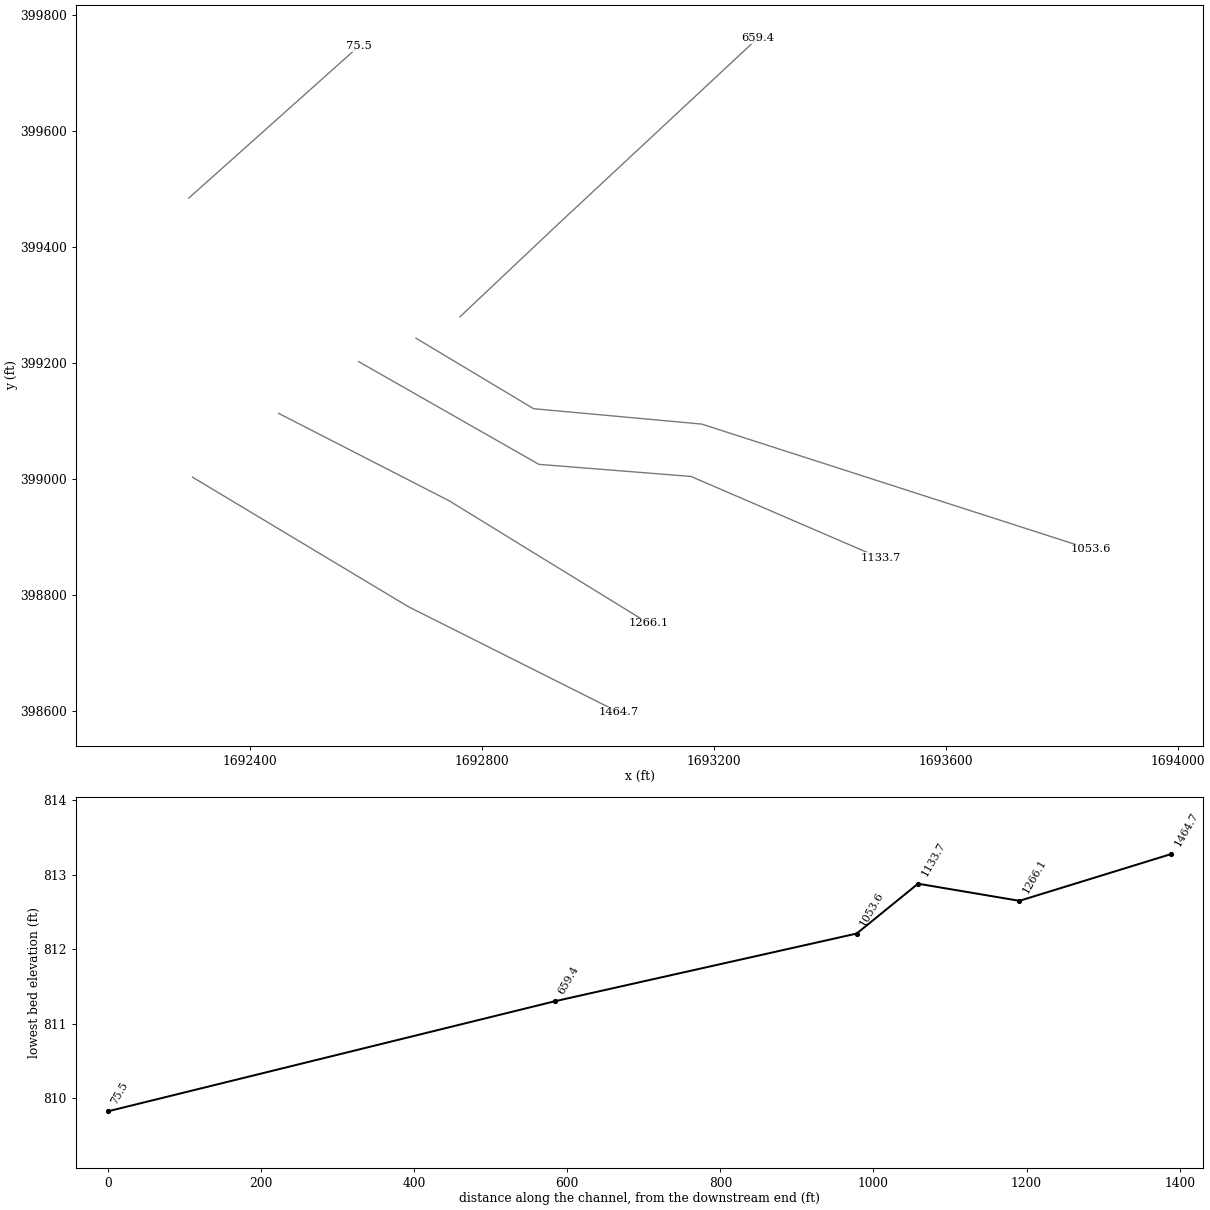
HEC-RAS study MUDRV.prj: MUDRV

--- MUDRV.g01 (geometry) --- (continued)

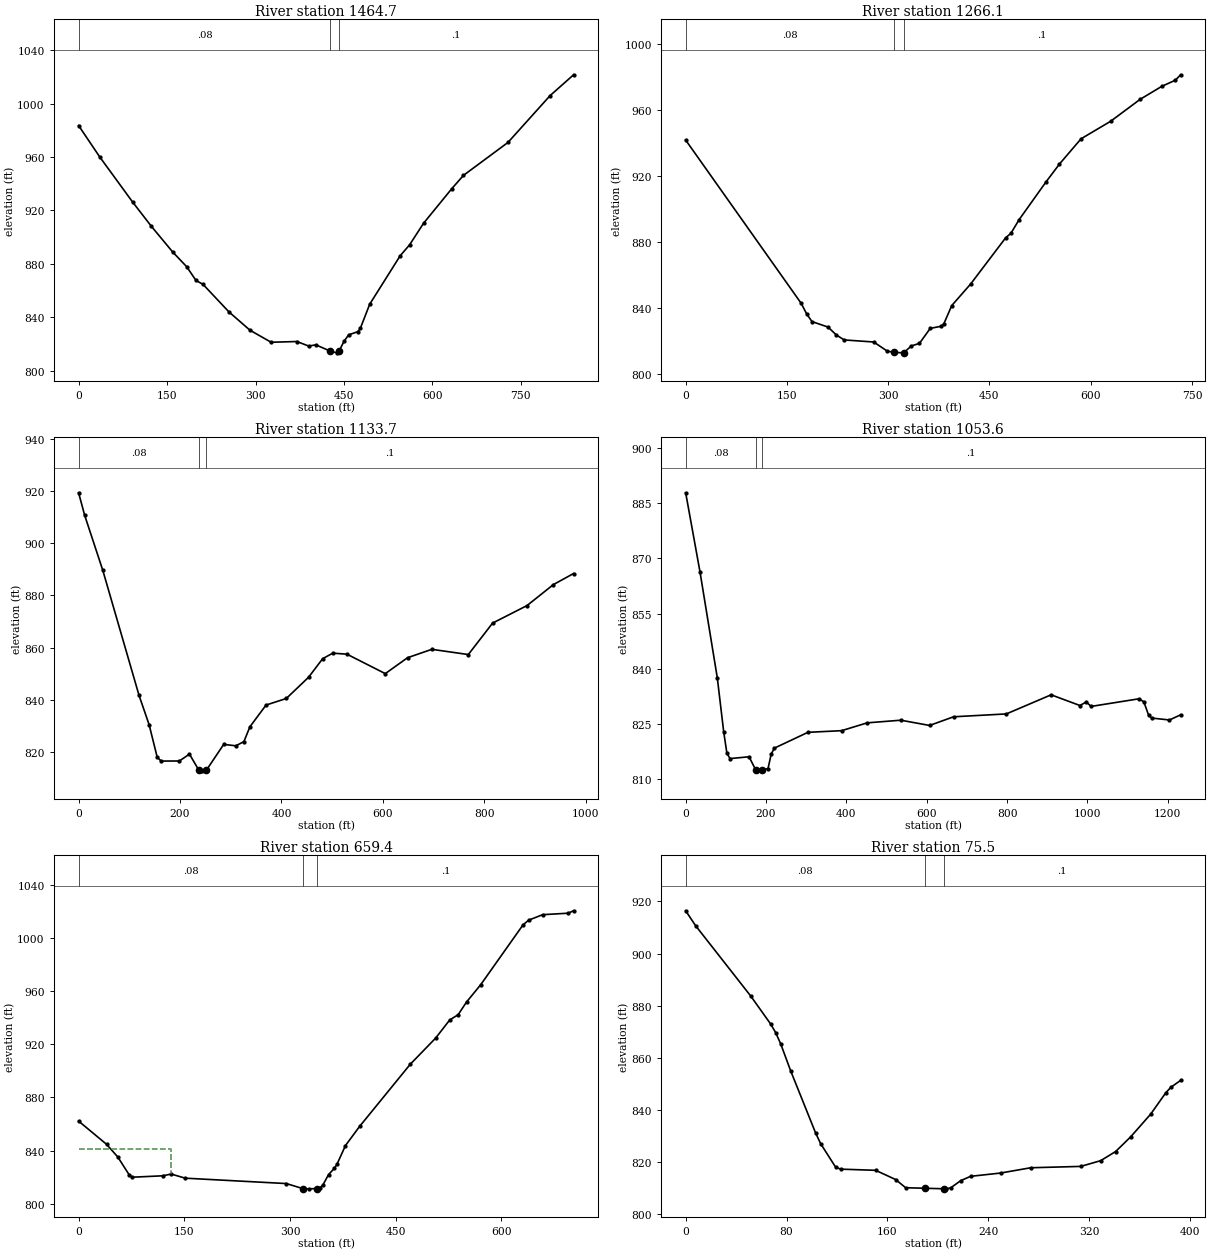
Type RM Length L Ch R = 1 ,1464.7  ,196.1,198.6,195.9
XS GIS Cut Line= 3
     1692300.602      399002.643      1692672.82      398779.363
     1693035.091      398597.585
#Sta/Elev= 30
       0  983.66    35.8  960.16    91.6  926.32   123.4  908.14   159.3  889.01
   183.2  877.88   199.1  867.52     211  864.61   254.9  843.99   290.7  830.21
   326.5  821.22   370.3  821.77   390.2  818.34   402.2  819.29   426.6  814.61
     438  813.28   441.6   814.5     450  821.84   457.9  826.75   473.8   829.2
   477.8   831.7   493.7  849.78   545.3  886.04   561.2  894.19     585  910.44
   632.7  936.27   652.6   946.3   728.1     971   799.6 1006.14   839.4 1021.73
#Mann= 3 , 0 , 0
       0     .08       0   426.6    .045       0   441.6      .1       0
Bank Sta=426.6,441.6
XS Rating Curve= 0 ,0
Exp/Cntr=0.3,0.1

Type RM Length L Ch R = 1 ,1266.1  ,133.8,132.4,132.9
XS GIS Cut Line= 3
     1692449.154      399112.559     1692743.142      398961.883
     1693086.473      398751.017
#Sta/Elev= 30
       0  941.83   171.2  842.66   179.1  836.37   187.1  831.63     211  828.28
   222.9  823.59   234.8  820.49   278.6  819.23   298.5  813.73   308.3  812.94
   322.4  812.65   323.3  812.84   334.3  816.83   346.3  818.38   362.3  827.49
   378.2  828.77   382.2  830.04   394.2  841.36   422.1  854.41     474  882.48
   481.9  885.27   493.9  893.47   533.8  916.42   553.8   927.3   585.7  942.59
   629.6  953.25   673.4   966.6   705.3  974.44   725.3  978.15   733.3  981.47
#Mann= 3 , 0 , 0
       0     .08       0   308.3    .045       0   323.3      .1       0
Bank Sta=308.3,323.3
XS Rating Curve= 0 ,0
Exp/Cntr=0.3,0.1

Type RM Length L Ch R = 1 ,1133.7  ,80.9,80.1,79.3
XS GIS Cut Line= 4
     1692587.174      399201.752     1692897.938      399024.668
     1693160.091      399003.835      1693486.48       398863.21
#Sta/Elev= 30
       0  919.31    11.9  910.72    47.7  889.63   119.2  841.73   139.1   830.5
     155  818.06   162.9  816.62   198.7  816.65   218.6  819.28   236.6  813.28
   242.4  812.88   251.6  813.02   286.1  823.01     310  822.46   325.9  824.06
   337.8  829.75   369.6  838.06   409.5  840.57   453.3  848.67   481.2   855.8
   501.1  857.92     529  857.54   604.7  850.09   648.6  856.18   696.5  859.39
   768.4  857.39   816.3  869.43   884.2  876.14   936.1  884.16     976  888.41
#Mann= 3 , 0 , 0
       0     .08       0   236.6    .045       0   251.6      .1       0
Bank Sta=236.6,251.6
XS Rating Curve= 0 ,0
Exp/Cntr=0.3,0.1

Type RM Length L Ch R = 1 ,1053.6  ,339.3,394.2,443.5
XS GIS Cut Line= 4
     1692685.916      399242.116     1692888.824      399120.589
     1693178.599      399094.091     1693849.172      398878.162
#Sta/Elev= 30
       0  887.88    35.5  866.45    78.8  837.47    94.6  822.86   102.5  817.07
   110.4  815.54   157.7  816.04   174.5  812.43   177.4  812.21   189.5  812.42
     205  812.84   212.9  816.79   220.8  818.39   304.3  822.69     388  823.14
   451.8  825.27   535.5  825.99   607.1  824.56   666.8  826.92   798.2   827.7
   909.6   832.9   981.2  829.99   997.2  830.95  1009.1  829.74  1128.5  831.82
  1140.4  830.98  1152.4   827.3  1160.3  826.57  1204.1  826.05    1232  827.46
#Mann= 3 , 0 , 0
       0     .08       0   174.5    .045       0   189.5      .1       0
Bank Sta=174.5,189.5
XS Rating Curve= 0 ,0
Exp/Cntr=0.3,0.1

Type RM Length L Ch R = 1 ,659.4   ,594.4,583.9,580.3
XS GIS Cut Line= 3
     1692761.871      399279.009     1692932.696      399440.222
     1693274.986       399759.04
#Sta/Elev= 30
       0  862.24    39.8  844.74    55.7   835.2    71.7  821.91    75.6  820.04
   119.4   821.1   131.4  822.42   151.3  819.32   294.9  815.27   318.8  811.39
   326.8   811.3   338.8  811.49   342.8  812.09   346.8  814.23   354.8  822.03
   362.8   826.6   366.8  829.85   378.8  843.86   398.8  858.21   470.8  905.01
   506.8  924.67   526.7  938.26   538.7  942.24   550.7  951.83   570.7  964.77
   630.7 1009.71   638.7 1013.33   658.7 1017.46   694.7 1018.58   702.6  1020.4
#Mann= 3 , 0 , 0
       0     .08       0   318.8    .045       0   338.8      .1       0
#XS Ineff= 2 , 0
          131.15  841.37
Permanent Ineff=
       F       F
Bank Sta=318.8,338.8
XS Rating Curve= 0 ,0
Exp/Cntr=0.3,0.1

Type RM Length L Ch R = 1 ,75.5    ,61.3,75.5,87.3
XS GIS Cut Line= 2
     1692294.083      399483.432     1692587.051      399744.934
#Sta/Elev= 30
       0  916.41     7.9  910.68    51.6  883.74    67.4  873.01    71.4   869.7
    75.4  865.38    83.3  855.04   103.1  831.22   107.1  827.12     119   818.1
     123  817.37   150.7  816.92   166.6  813.38   174.5  810.25   189.7  810.04
   204.7  809.85   206.3  809.82   210.2  810.18   218.2  812.96   226.1  814.62
   249.9  815.88   273.7   817.9   313.4  818.42   329.2  820.61   341.1  824.12
     353  829.73   368.9  838.45   380.8  846.58   384.8   848.7   392.7  851.41
#Mann= 3 , 0 , 0
       0     .08       0   189.7    .045       0   204.7      .1       0
Bank Sta=189.7,204.7
XS Rating Curve= 0 ,0
Exp/Cntr=0.3,0.1

Chan Stop Cuts=-1
Use User Specified Reach Order=0
Composite Channel Slope=5